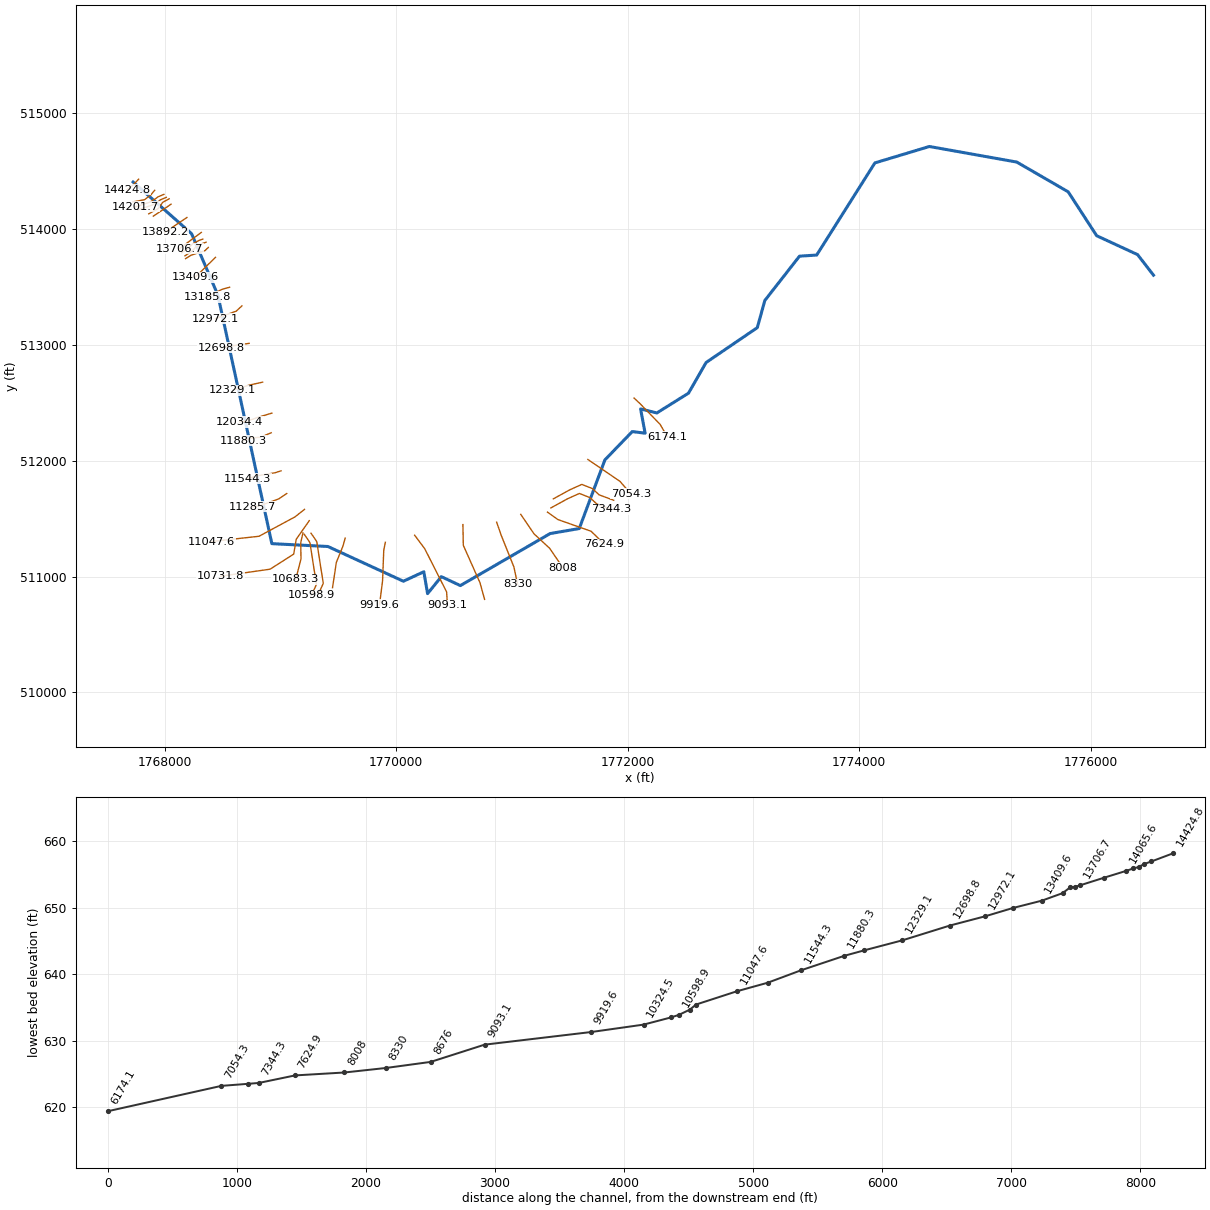
--- TWOMILECK.prj (project) ---

Proj Title=TWOMILECK
Current Plan=p01
Default Exp/Contr=0,0
English Units
Geom File=g01
Flow File=f01
Plan File=p01
BEGIN DESCRIPTION:
END DESCRIPTION:
DSS Export Rating Curves= 0
DSS Export Rating Curve Sorted= 0
DSS Export Volume Flow Curves= 0
DXF OffsetX= 0
DXF OffsetY= 0
DXF ScaleX= 0
DXF ScaleY= 0

--- TWOMILECK.p01 (plan) ---

Plan Title=Floodplain
Program Version=4.00
Geom File=g01
Flow File=f01
K Sum by GR=0
Std Step Tol=0.01
Critical Tol=0.01
Num of Std Step Trials=20
Max Error Tol=0.3
Flow Tol Ratio=0.001
Split Flow NTrial=30
Split Flow Tol=0.02
Split Flow Ratio=0.02
Log Output Level=0
Friction Slope Method=1
Unsteady Friction Slope Method=2
Unsteady Bridges Friction Slope Method=1
Global Log Level=0
CheckData=False
Run HTab=0
Run UNet=0
Run PostProcess=0
UNET Theta=0
UNET Theta Warmup=0
UNET ZTol=0
UNET ZSATol=0
UNET MxIter=0
UNET MaxInSteps=0
UNET DtIC=0
UNET DtMin=0
UNET MaxCRTS=0
UNET WFStab=0
UNET SFStab=0
UNET WFX=0
UNET SFX=0
UNET DSS MLevel=0
UNET DZMax Abort=0
UNET Convert EG Bridges=0
UNET Use Existing IB Tables=0
UNET Froude Limit=0
UNET Froude Power=0
Write IC File=0
Echo Input=False
Echo Output=False
Write Detailed=0

--- TWOMILECK.f01 (steady flow) ---

Flow Title=NFF Regression Equation
Program Version=4.10
Number of Profiles= 1
Profile Names=P100yr
River Rch & RM=TWOMILECK,Main            ,14424.8
862.8471
River Rch & RM=TWOMILECK,Main            ,13892.2
914.1602
River Rch & RM=TWOMILECK,Main            ,13185.8
962.2139
River Rch & RM=TWOMILECK,Main            ,11285.7
1003.449
River Rch & RM=TWOMILECK,Main            ,10731.8
1304.582
River Rch & RM=TWOMILECK,Main            ,10324.5
1462.053
River Rch & RM=TWOMILECK,Main            ,7054.3
1572.296
River Rch & RM=TWOMILECK,Main            ,5460.7
1635.572
River Rch & RM=TWOMILECK,Main            ,4089.7
  1704.3
Boundary for River Rch & Prof#=TWOMILECK,Main            , 1
Up Type= 0
Dn Type= 3
Dn Slope=0.0035
DSS Import GetInterval= 0
DSS Import GetPeak= 0
DSS Import FillOption= 0

--- TWOMILECK.g01 (geometry) ---

Geom Title=USGS 10m DEM
Program Version=4.10

River Reach=TWOMILECK       ,Main
Reach XY= 30
     1767725.983      514406.378     1768230.541      513961.066
     1768458.405      513429.381     1768924.758        511283.9
     1769408.926      511259.243     1770061.502      510959.316
     1770237.919      511041.144     1770270.471      510852.342
     1770389.244      510998.911     1770553.674      510921.786
     1771329.499      511371.005     1771581.235      511414.408
     1771802.695      512006.886     1772039.322      512251.719
     1772150.434      512237.831     1772111.371      512447.032
     1772251.896      512412.575     1772525.434      512583.317
     1772677.343      512848.074     1773120.051      513149.289
     1773185.074      513383.839     1773484.635      513766.476
     1773633.072      513776.025     1774136.125      514571.808
     1774607.031      514713.525     1775362.239      514578.976
     1775806.684      514322.032     1776052.774      513942.976
      1776406.51      513779.497     1776543.563      513602.573

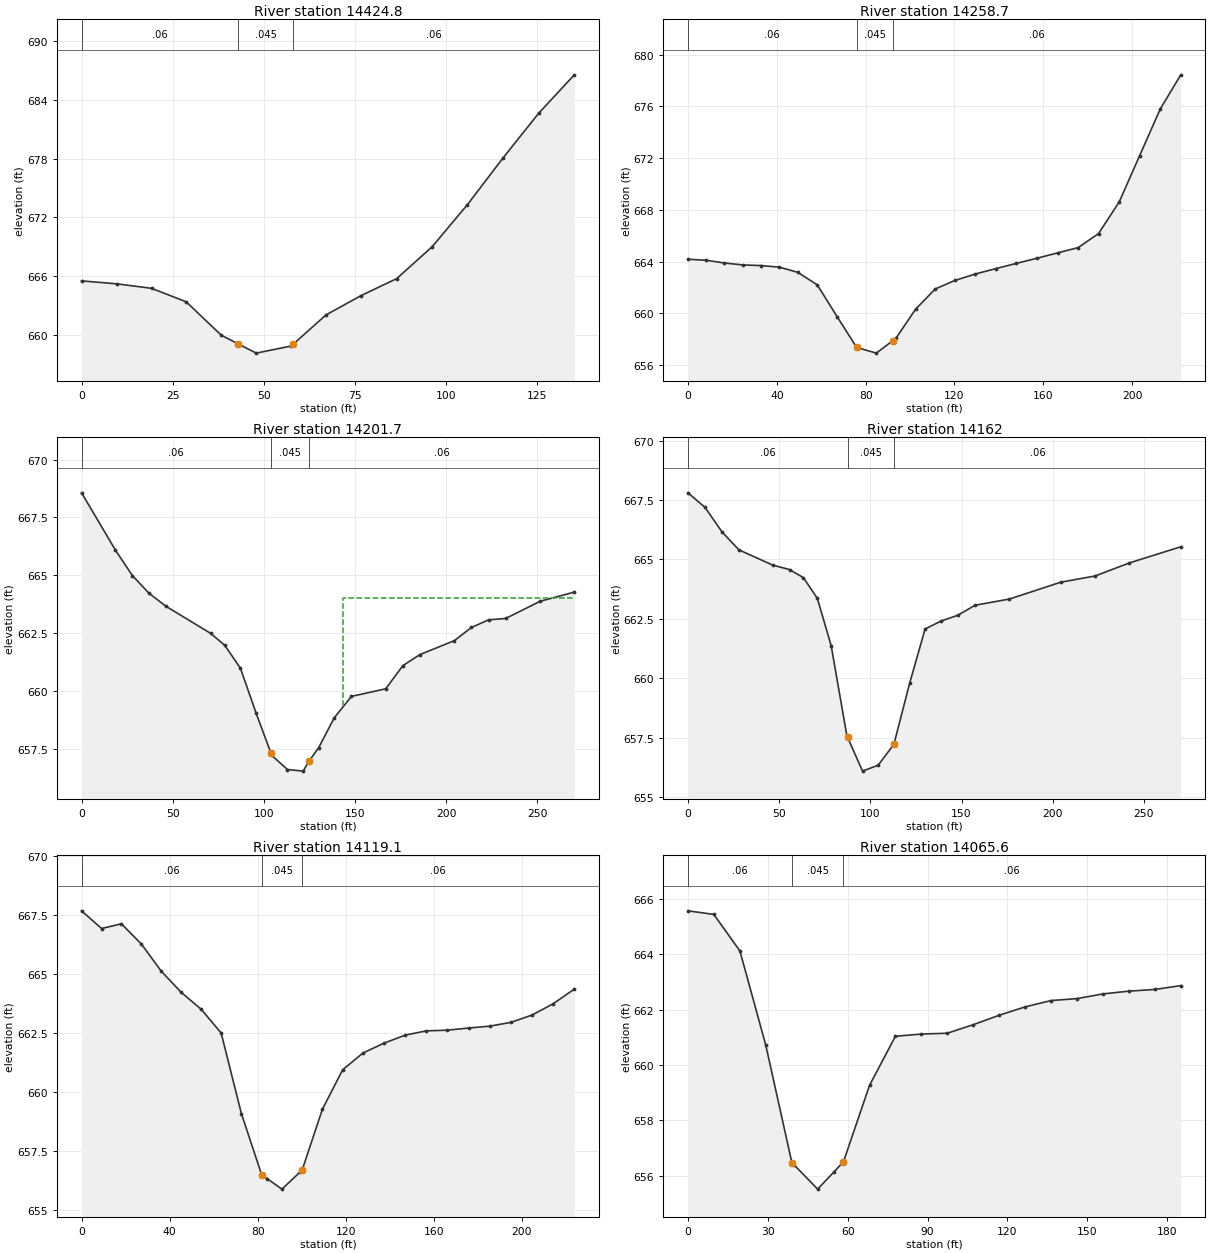
Type RM Length L Ch R = 1 ,14424.8 ,169.4,166.2,162.9
XS GIS Cut Line= 3
     1767773.807      514431.212     1767720.335      514376.351
     1767673.807      514340.934
#Sta/Elev= 17
       0  665.51     9.6  665.21    19.2  664.75    28.7  663.37    38.3  659.96
      43  659.06    47.9  658.13    57.5  658.86      58  659.03      67  662.03
    76.6     664    86.4  665.74    96.1  668.99   105.8   673.3   115.6  678.09
   125.3  682.62   135.1  686.56
#Mann= 3 , 0 , 0
       0     .06       0      43    .045       0      58     .06       0
Bank Sta=43,58
XS Rating Curve= 0 ,0
Exp/Cntr=0.3,0.1

Type RM Length L Ch R = 1 ,14258.7 ,68.1,57,43
XS GIS Cut Line= 4
     1767912.002      514335.379     1767880.752      514297.184
     1767824.502      514254.129     1767724.502      514235.379
#Sta/Elev= 28
       0  664.18     8.2   664.1    16.4  663.89    24.7  663.74    32.9  663.69
    41.1  663.57    49.4  663.17    58.2   662.2    67.1  659.75    75.9  657.37
    77.2   657.3    84.8  656.92    92.2  657.88    93.6  658.06   102.5  660.32
   111.3  661.88   120.2  662.54   129.4  663.04   138.7  663.46   147.9  663.86
   157.2  664.26   166.4  664.67   175.7  665.08   184.9  666.17   194.2  668.62
   203.4   672.2   212.7  675.81   221.9  678.44
#Mann= 3 , 0 , 0
       0     .06       0    75.9    .045       0    92.2     .06       0
Bank Sta=75.9,92.2
XS Rating Curve= 0 ,0
Exp/Cntr=0.3,0.1

Type RM Length L Ch R = 1 ,14201.7 ,34.7,39.7,52
XS GIS Cut Line= 5
     1767991.863      514299.962     1767940.474      514278.434
     1767922.418      514264.545     1767871.029      514233.295
     1767746.029      514192.323
#Sta/Elev= 26
       0  668.56    18.6  666.08    27.9  664.98    37.1  664.21    46.4  663.65
    70.9  662.48    78.5  661.97    87.1  660.98    95.7  659.04   103.9   657.3
   104.3  657.21   112.9   656.6   121.5  656.53  124.89  656.98     130  657.54
   138.6  658.84     148  659.76   166.8  660.09   176.2  661.09   185.6  661.57
   204.4  662.17   213.8  662.74   223.2  663.07   232.6  663.13   251.4  663.87
   270.2  664.27
#Mann= 3 , 0 , 0
       0     .06       0   103.9    .045       0  124.89     .06       0
#XS Ineff= 2 , 0
                          143.63          664.03
Permanent Ineff=
       F       F
Bank Sta=103.9,124.89
XS Rating Curve= 0 ,0
Exp/Cntr=0.3,0.1

Type RM Length L Ch R = 1 ,14162   ,34.1,42.8,52.6
XS GIS Cut Line= 5
     1768012.696      514274.268     1767961.307       514252.74
     1767943.252      514238.851     1767891.863      514207.601
     1767766.863      514166.629
#Sta/Elev= 24
       0   667.8     9.3  667.19    18.6  666.16    27.9   665.4    46.4  664.76
    55.7  664.57    63.3  664.23    70.9  663.36    78.5  661.37    87.1  657.58
    87.5  657.51    95.7  656.09   104.3  656.34   112.9  657.22   121.5  659.78
     130  662.07   138.6   662.4     148  662.65   157.4  663.07   176.2  663.33
   204.4  664.04   223.2   664.3     242  664.85   270.2  665.53
#Mann= 3 , 0 , 0
       0     .06       0    87.5    .045       0   112.9     .06       0
Bank Sta=87.5,112.9
XS Rating Curve= 0 ,0
Exp/Cntr=0.3,0.1

Type RM Length L Ch R = 1 ,14119.1 ,62.3,53.5,44.3
XS GIS Cut Line= 4
     1768037.002      514261.768     1767981.446      514231.212
     1767944.641      514178.434     1767860.613      514131.907
#Sta/Elev= 27
       0  667.68     9.1  666.93    18.1  667.13    27.2  666.27    36.2  665.12
    45.3  664.22    54.4   663.5    63.4   662.5    72.6  659.08    81.8  656.49
    84.2  656.33      91  655.88    99.2   656.6   100.2  656.69   109.4  659.27
   118.6  660.94   127.8  661.65   137.4  662.07     147  662.41   156.6  662.59
   166.2  662.62   175.8  662.71   185.4  662.79     195  662.95   204.6  663.26
   214.2  663.74   223.8  664.36
#Mann= 3 , 0 , 0
       0     .06       0    81.8    .045       0   100.2     .06       0
Bank Sta=81.8,100.2
XS Rating Curve= 0 ,0
Exp/Cntr=0.3,0.1

Type RM Length L Ch R = 1 ,14065.6 ,172.6,173.3,173.7
XS GIS Cut Line= 2
     1768053.668       514215.24     1767900.196      514111.768
#Sta/Elev= 22
       0  665.57     9.7  665.44    19.5  664.12    29.2  660.72      39  656.48
    39.8   656.4    48.7  655.52    54.8  656.14    58.4  656.51    68.2  659.27
    77.9  661.04    87.7  661.12    97.4  661.15   107.2  661.46   116.9   661.8
   126.6   662.1   136.4  662.33   146.1   662.4   155.9  662.57   165.6  662.67
   175.4  662.73   185.1  662.87
#Mann= 3 , 0 , 0
       0     .06       0      39    .045       0    58.4     .06       0
Bank Sta=39,58.4
XS Rating Curve= 0 ,0
Exp/Cntr=0.3,0.1

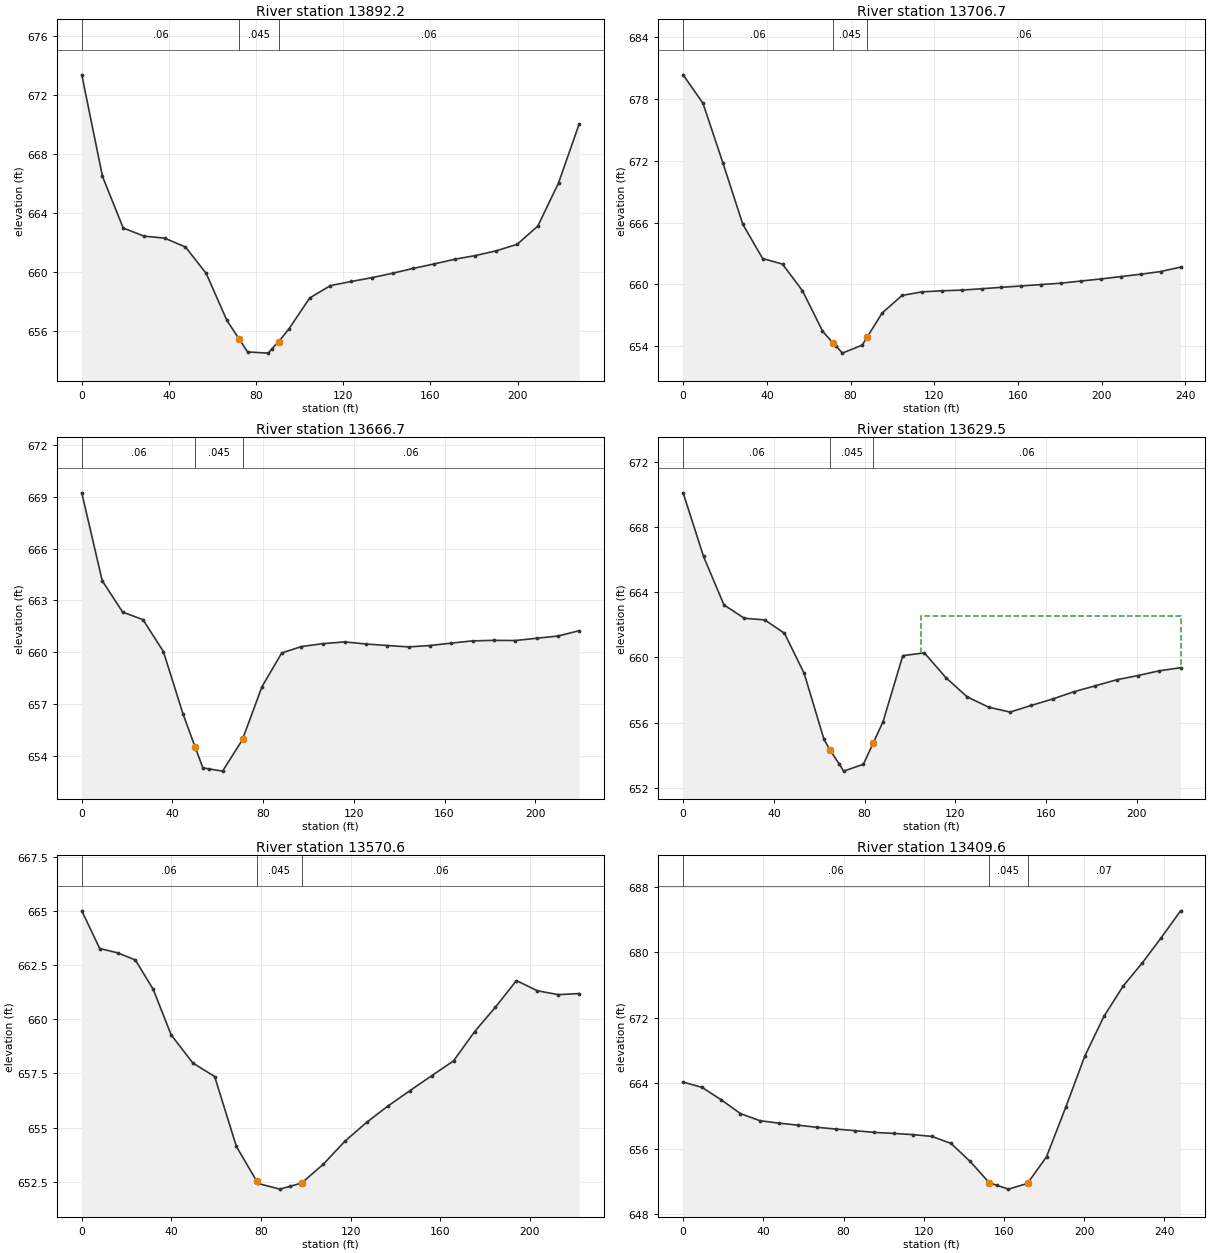
Type RM Length L Ch R = 1 ,13892.2 ,184.7,185.6,186.7
XS GIS Cut Line= 2
       1768190.3      514100.309     1768000.891      513972.879
#Sta/Elev= 28
       0  673.36     9.5  666.47      19  662.97    28.5  662.42      38  662.28
    47.6  661.68    57.1  659.89    66.6   656.7    72.3  655.42    76.1  654.56
    85.6  654.48    87.3  654.78   90.35  655.26    95.1  656.13   104.6  658.22
   114.1  659.06   123.7  659.34   133.2   659.6   142.7   659.9   152.2  660.23
   161.7  660.53   171.2  660.85   180.7   661.1   190.2  661.42   199.8  661.86
   209.3   663.1   218.8  666.02   228.3  670.03
#Mann= 3 , 0 , 0
       0     .06       0    72.3    .045       0   90.35     .06       0
Bank Sta=72.3,90.35
XS Rating Curve= 0 ,0
Exp/Cntr=0.3,0.1

Type RM Length L Ch R = 1 ,13706.7 ,43.3,39.9,36.5
XS GIS Cut Line= 2
       1768315.3      513971.837     1768124.328      513830.344
#Sta/Elev= 29
       0  680.32     9.5  677.56      19  671.79    28.5  665.84      38  662.51
    47.5  661.97      57   659.4    66.6  655.49   71.52  654.33    73.1  654.02
    76.1  653.34    85.6  654.12    88.1  654.94    95.1  657.23   104.6  658.93
   114.1  659.28   123.6  659.38   133.1  659.45   142.6  659.58   152.1  659.72
   161.6  659.85   171.1  659.99   180.6  660.12   190.1  660.33   199.6  660.53
   209.2  660.76   218.7  660.99   228.2  661.25   237.7  661.68
#Mann= 3 , 0 , 0
       0     .06       0   71.52    .045       0    88.1     .06       0
Bank Sta=71.52,88.1
XS Rating Curve= 0 ,0
Exp/Cntr=0.3,0.1

Type RM Length L Ch R = 1 ,13666.7 ,37.2,37.2,37.9
XS GIS Cut Line= 5
     1768327.453      513913.677     1768293.599      513901.525
     1768239.779      513872.879     1768207.661      513838.157
     1768145.161       513796.49
#Sta/Elev= 28
       0  669.23       9  664.14      18  662.32      27  661.88      36  660.03
    44.7  656.39   50.04  654.48    53.4  653.29      56  653.23    62.1   653.1
    70.8  654.91      71  654.98    79.5     658    88.2  659.95    96.9  660.32
   106.4  660.49   115.9  660.59   125.3  660.47   134.8  660.38   144.2   660.3
   153.6  660.38     163  660.52   172.4  660.65   181.8  660.68   191.2  660.67
   200.6   660.8     210  660.93   219.4  661.24
#Mann= 3 , 0 , 0
       0     .06       0   50.04    .045       0      71     .06       0
Bank Sta=50.04,71
XS Rating Curve= 0 ,0
Exp/Cntr=0.3,0.1

Type RM Length L Ch R = 1 ,13629.5 ,62.8,58.9,54.5
XS GIS Cut Line= 5
     1768356.099      513886.768     1768322.245      513874.615
     1768268.425      513845.969     1768236.307      513811.247
     1768173.807       513769.58
#Sta/Elev= 28
       0  670.09       9  666.19      18  663.22      27   662.4      36   662.3
    44.7  661.48    53.4  659.02    62.1  654.99   64.88   654.3    68.8  653.48
    70.8  653.03    79.5  653.45    83.8  654.74    88.2  656.07    96.9  660.11
   106.4  660.28   115.9  658.76   125.3  657.58   134.8  656.95   144.2  656.65
   153.6  657.06     163  657.45   172.4   657.9   181.8  658.26   191.2  658.63
   200.6  658.89     210  659.18   219.4  659.37
#Mann= 3 , 0 , 0
       0     .06       0   64.88    .045       0    83.8     .06       0
#XS Ineff= 2 , 0
                          104.99          662.57
Permanent Ineff=
       F       F
Bank Sta=64.88,83.8
XS Rating Curve= 0 ,0
Exp/Cntr=0.3,0.1

Type RM Length L Ch R = 1 ,13570.6 ,150.4,161,171.3
XS GIS Cut Line= 4
     1768375.196      513841.629      1768346.55      513813.851
     1768226.759      513774.788     1768179.016      513745.275
#Sta/Elev= 27
       0  665.01       8  663.27      16  663.07    23.9  662.74    31.9  661.38
    39.9  659.28    49.6  657.98    59.3  657.36      69  654.13      78  652.54
    78.7  652.42    88.4  652.16      93  652.29    98.1  652.44   107.8  653.31
   117.4  654.37   127.1  655.24   136.8  656.01   146.5  656.71   156.2   657.4
   165.9  658.08   175.3  659.43   184.6  660.56     194  661.79   203.3  661.32
   212.7  661.14     222  661.19
#Mann= 3 , 0 , 0
       0     .06       0      78    .045       0    98.1     .06       0
Bank Sta=78,98.1
XS Rating Curve= 0 ,0
Exp/Cntr=0.3,0.1

Type RM Length L Ch R = 1 ,13409.6 ,231.4,223.8,216.2
XS GIS Cut Line= 2
     1768437.696      513756.559     1768260.613      513582.948
#Sta/Elev= 28
       0  664.13     9.5  663.47    19.1  661.94    28.6  660.27    38.2  659.41
    47.7   659.1    57.2  658.86    66.8  658.59    76.3  658.38    85.8  658.18
    95.4  657.97   104.9  657.85   114.5   657.7     124  657.48   133.5  656.63
   143.1  654.42   152.6  651.82   156.7  651.48   162.2  651.03   171.7  651.73
   181.2     655   190.8  661.07   200.3  667.33   209.8  672.17   219.4  675.88
   228.9   678.7   238.4   681.8     248  685.08
#Mann= 3 , 0 , 0
       0     .06       0   152.6    .045       0   171.7     .07       0
Bank Sta=152.6,171.7
XS Rating Curve= 0 ,0
Exp/Cntr=0.3,0.1

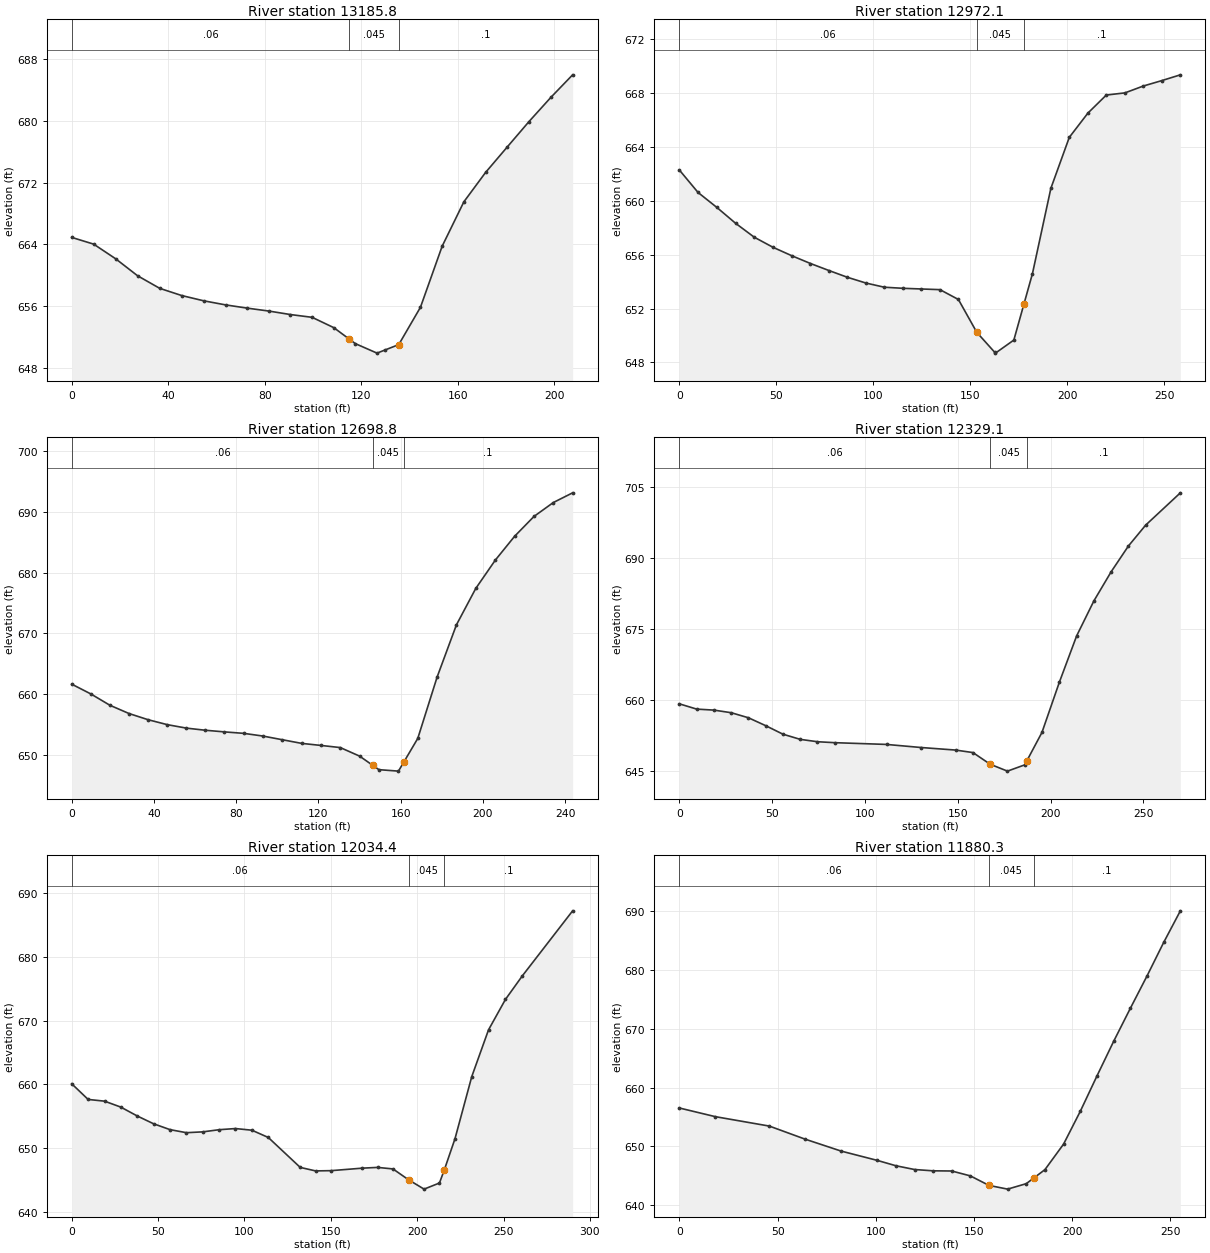
Type RM Length L Ch R = 1 ,13185.8 ,215.9,213.7,211.3
XS GIS Cut Line= 4
     1768559.224      513497.879     1768497.592      513481.386
     1768424.675      513446.663     1768370.856      513413.677
#Sta/Elev= 26
       0   664.9     9.1  664.03    18.2  662.14    27.3  659.94    36.5  658.31
    45.6  657.38    54.7   656.7    63.8  656.17    72.8  655.75    81.8  655.37
    90.7  654.92    99.7  654.56   108.7  653.22   115.1  651.74   117.6  651.16
   126.6  649.93   130.1  650.36   135.6  651.03   144.6  655.86   153.6  663.76
   162.6   669.5   171.6   673.3   180.6   676.6   189.6  679.88   198.7  683.02
   207.7  685.93
#Mann= 3 , 0 , 0
       0     .06       0   115.1    .045       0   135.6      .1       0
Bank Sta=115.1,135.6
XS Rating Curve= 0 ,0
Exp/Cntr=0.3,0.1

Type RM Length L Ch R = 1 ,12972.1 ,277,273.3,269.4
XS GIS Cut Line= 3
     1768665.995      513337.288     1768616.516      513291.282
     1768436.828      513227.045
#Sta/Elev= 30
       0  662.27     9.6  660.61    19.3   659.5      29  658.32    38.6  657.29
    48.3  656.54    57.9  655.92    67.6  655.34    77.1  654.82    86.6  654.32
    96.2  653.89   105.7  653.58   115.3   653.5   124.8  653.45   134.4   653.4
   143.9  652.67   153.4  650.23   162.7  648.74     163  648.69   172.5  649.66
   177.7  652.33   182.1  654.59   191.6  660.92   201.1   664.7   210.7   666.5
   220.2  667.84   229.8     668   239.3  668.51   248.8  668.91   258.4  669.34
#Mann= 3 , 0 , 0
       0     .06       0   153.4    .045       0   177.7      .1       0
Bank Sta=153.4,177.7
XS Rating Curve= 0 ,0
Exp/Cntr=0.3,0.1

Type RM Length L Ch R = 1 ,12698.8 ,366.5,369.7,372.3
XS GIS Cut Line= 3
     1768728.495      513013.504     1768636.481      513000.483
     1768488.043      512974.441
#Sta/Elev= 29
       0  661.62     9.3  660.01    18.6  658.14    27.9  656.78    37.2  655.76
    46.5  654.95    55.8  654.38      65  654.03    74.3  653.76    83.6  653.52
    92.9  653.08   102.4  652.47   111.8  651.87   121.2  651.53   130.6  651.18
     140  649.77   146.5  648.23   149.4  647.54   158.9   647.3   161.5  648.79
   168.3  652.69   177.7  662.79   187.1  671.39   196.5  677.38     206  682.04
   215.4  685.97   224.8  689.23   234.2  691.52   243.6  693.12
#Mann= 3 , 0 , 0
       0     .06       0   146.5    .045       0   161.5      .1       0
Bank Sta=146.5,161.5
XS Rating Curve= 0 ,0
Exp/Cntr=0.3,0.1

Type RM Length L Ch R = 1 ,12329.1 ,293.6,294.7,292.3
XS GIS Cut Line= 3
     1768844.814      512678.434     1768726.759      512652.393
     1768584.397      512608.122
#Sta/Elev= 26
       0  659.28     9.3  658.17    18.6  657.96    27.9  657.41    37.2  656.34
    46.5  654.67    55.8  652.87    65.1  651.78    74.4  651.28    83.7  651.08
   111.6  650.71   130.2  650.06   148.8  649.52   158.2  648.99   167.5  646.52
   176.8  645.07   186.1  646.39   187.3  647.28   195.4  653.25   204.8  663.88
   214.1  673.65   223.4  681.04   232.7  687.19     242  692.63   251.3  697.04
     270  703.86
#Mann= 3 , 0 , 0
       0     .06       0   167.5    .045       0   187.3      .1       0
Bank Sta=167.5,187.3
XS Rating Curve= 0 ,0
Exp/Cntr=0.3,0.1

Type RM Length L Ch R = 1 ,12034.4 ,160.1,154.2,151.5
XS GIS Cut Line= 4
     1768924.675      512411.073      1768806.62      512375.483
     1768713.738      512342.497     1768646.029      512334.684
#Sta/Elev= 29
       0  660.11     9.5  657.65      19  657.38    28.4  656.45    37.9  655.06
    47.4  653.83    56.9  652.91    66.4  652.43    75.9  652.56    85.4   652.9
    94.8  653.08   104.3  652.82   113.8  651.68   132.3  646.98   141.2  646.43
   150.2  646.47   168.1  646.86   177.1  646.98     186  646.74     195  645.04
     204  643.57   212.9  644.53  215.77  646.63   221.9  651.49   231.6  661.23
   241.3  668.57   251.1  673.35   260.8  677.02     290  687.26
#Mann= 3 , 0 , 0
       0     .06       0     195    .045       0  215.77      .1       0
Bank Sta=195,215.77
XS Rating Curve= 0 ,0
Exp/Cntr=0.3,0.1

Type RM Length L Ch R = 1 ,11880.3 ,333.6,336,338
XS GIS Cut Line= 4
     1768919.467      512241.802     1768826.585       512202.74
     1768731.967      512194.927     1768677.279       512171.49
#Sta/Elev= 24
       0  656.53    18.3  655.06    45.8  653.46    64.1  651.23    82.4  649.21
   100.8  647.63   110.3  646.72   119.8  646.08   129.2  645.86   138.7  645.83
   148.2     645   157.7  643.38   167.2  642.75   176.7  643.68   180.5  644.63
   186.2  646.06   195.7   650.4   204.2  655.96   212.7  661.97   221.2  667.85
   229.7  673.46   238.2  678.96   246.7  684.66   255.2  690.03
#Mann= 3 , 0 , 0
       0     .06       0   157.7    .045       0   180.5      .1       0
Bank Sta=157.7,180.5
XS Rating Curve= 0 ,0
Exp/Cntr=0.3,0.1

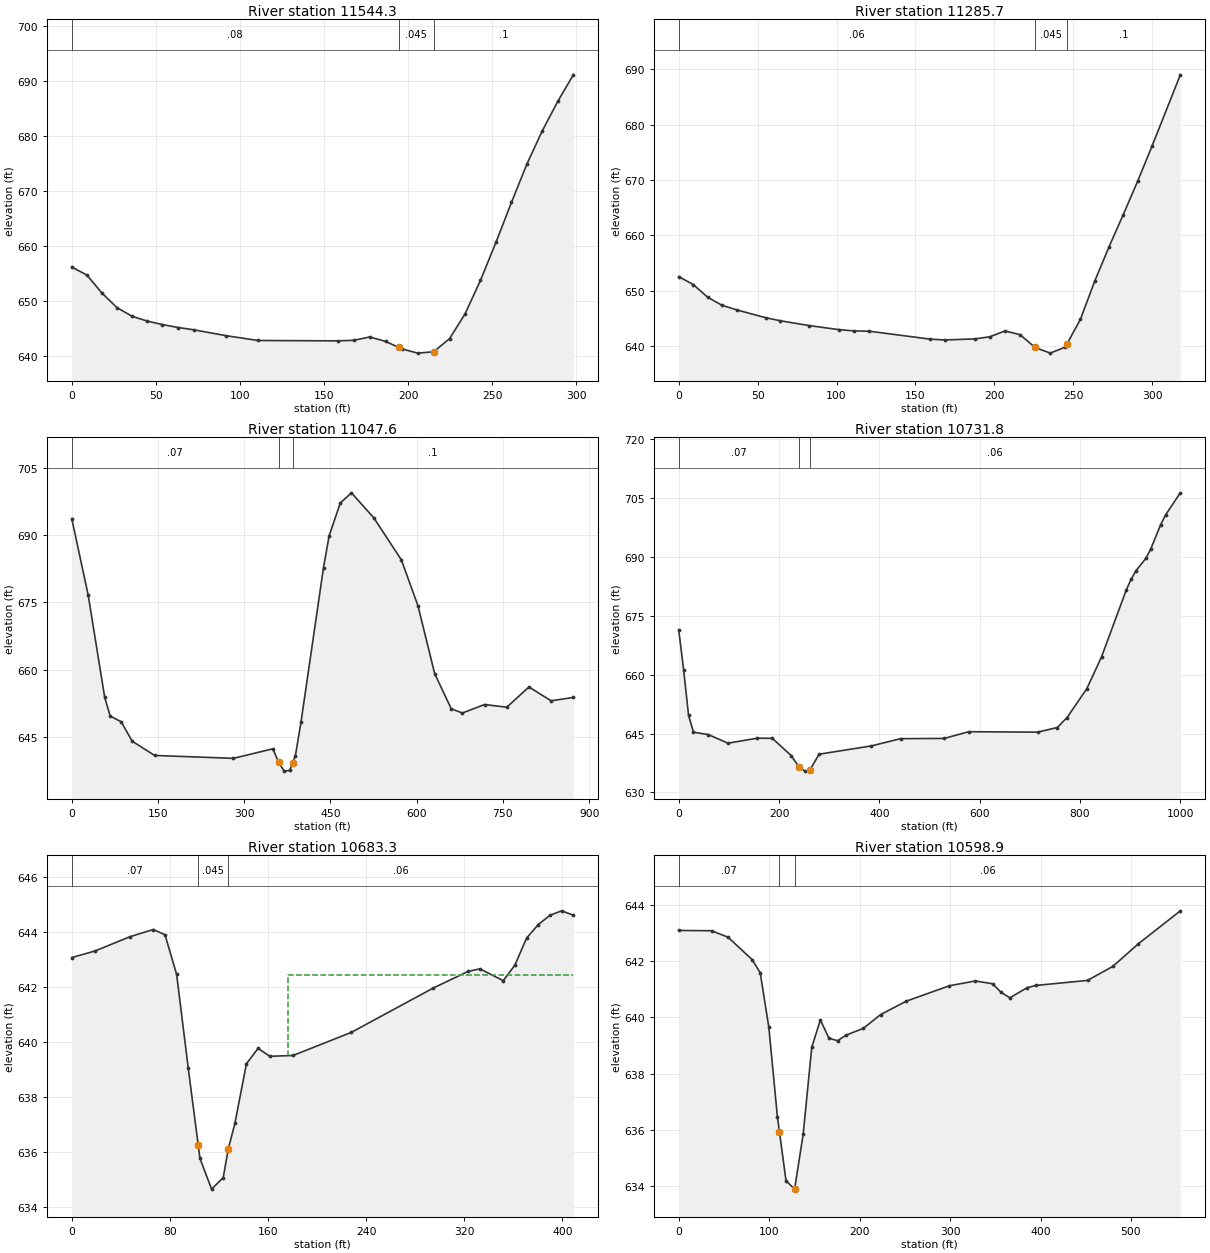
Type RM Length L Ch R = 1 ,11544.3 ,254.4,258.5,261.3
XS GIS Cut Line= 4
     1769004.536      511912.809     1768953.321      511896.316
     1768784.918       511867.67     1768715.474      511843.365
#Sta/Elev= 28
       0  656.22       9  654.78    17.9  651.52    26.9  648.84    35.9  647.27
    44.8  646.41    53.8  645.77    63.3  645.23    72.8   644.8    91.8  643.74
   110.8  642.87   158.2   642.8   167.7   642.9   177.2  643.51   186.7  642.69
   194.4   641.6   196.2  641.35   205.6  640.57   215.1  640.81   224.6   643.2
   233.8   647.7     243  653.82   252.2  660.73   261.4  667.98   270.6  674.98
   279.8  681.05     289   686.4   298.2   691.2
#Mann= 3 , 0 , 0
       0     .08       0   194.4    .045       0   215.1      .1       0
Bank Sta=194.4,215.1
XS Rating Curve= 0 ,0
Exp/Cntr=0.3,0.1

Type RM Length L Ch R = 1 ,11285.7 ,234.9,238.2,242.6
XS GIS Cut Line= 4
     1769053.147      511716.629     1768984.571      511670.622
     1768823.113      511611.594     1768760.613      511601.177
#Sta/Elev= 28
       0  652.53     9.2   651.1    18.4  648.79    27.5  647.34    36.7  646.52
      55  645.11    64.2  644.56    82.6  643.68   101.7  642.94   111.2  642.72
   120.8  642.66     159  641.24   168.5  641.08   187.6  641.27   197.2  641.66
   206.7  642.72   216.3  642.03   225.8  639.72   235.4   638.7   244.9  639.79
     246  640.37   254.5  644.82   263.5  651.67   272.6  657.91   281.6  663.72
   290.7  669.75   299.8  676.09   317.8  689.02
#Mann= 3 , 0 , 0
       0     .06       0   225.8    .045       0     246      .1       0
Bank Sta=225.8,246
XS Rating Curve= 0 ,0
Exp/Cntr=0.3,0.1

Type RM Length L Ch R = 1 ,11047.6 ,294.7,315.8,336.7
XS GIS Cut Line= 4
     1769206.793       511579.91     1769124.328      511514.806
     1768813.998      511347.705     1768401.672      511302.132
#Sta/Elev= 30
       0  693.69    28.6  676.64    57.3  653.86    66.9  649.69      86  648.42
   105.1  644.09   144.2  640.91   281.3  640.27   349.8   642.4   359.6  639.43
   369.4  637.42   379.2  637.58     384   639.2     389  640.88   398.8   648.4
   437.9  682.79   447.7  689.88   467.2  697.19   486.5  699.43   525.1   693.9
   573.3  684.49   602.2  674.25   631.2  659.15   660.1  651.31   679.4  650.37
     718  652.26   756.6  651.66   795.2  656.17   833.8  653.09   872.4  653.84
#Mann= 3 , 0 , 0
       0     .07       0   359.6    .045       0     384      .1       0
Bank Sta=359.6,384
XS Rating Curve= 0 ,0
Exp/Cntr=0.3,0.1

Type RM Length L Ch R = 1 ,10731.8 ,44.5,48.5,52.7
XS GIS Cut Line= 5
     1769248.026      511482.254     1769135.179      511321.663
     1769113.477      511193.625     1768909.484      511063.417
     1768481.967      511002.653
#Sta/Elev= 30
       0  671.37     9.8  661.21    19.6  649.62    29.4  645.35    58.9  644.74
    98.1  642.55     157  643.83   186.5  643.79   224.1   639.4   239.8  636.47
   251.9  635.43   261.2  635.66   279.8  639.74   384.2  641.86   442.3   643.7
   529.4  643.76     578  645.47   715.4  645.36   754.6  646.54   774.2  649.09
   813.5  656.42   842.9  664.53     892  681.52   901.8  684.28   911.6  686.49
   931.3  689.64   941.1  692.05   960.7  698.19   970.5  700.69    1000  706.33
#Mann= 3 , 0 , 0
       0     .07       0   239.8    .045       0   261.2     .06       0
Bank Sta=239.8,261.2
XS Rating Curve= 0 ,0
Exp/Cntr=0.3,0.1

Type RM Length L Ch R = 1 ,10683.3 ,81.3,84.4,87.5
XS GIS Cut Line= 4
     1769193.772      511377.219     1769174.675      511293.886
     1769176.411      511151.525     1769131.272      510976.177
#Sta/Elev= 28
       0  643.08      19  643.32    47.5  643.84    66.5   644.1      76  643.91
    85.5  642.47      95  639.05   103.1  636.26   104.5  635.78     114  634.66
   123.5  635.08  127.55  636.11     133  637.05   142.4  639.22   151.9  639.78
   161.4  639.49   180.4  639.52   227.9  640.36   294.6  641.97   323.2  642.58
   332.7  642.67   351.8  642.24   361.3  642.81   370.8  643.79   380.3  644.28
   389.9  644.62   399.4  644.78   408.9  644.62
#Mann= 3 , 0 , 0
       0     .07       0   103.1    .045       0  127.55     .06       0
#XS Ineff= 2 , 0
                          176.54          642.46
Permanent Ineff=
       F       F
Bank Sta=103.1,127.55
XS Rating Curve= 0 ,0
Exp/Cntr=0.3,0.1

Type RM Length L Ch R = 1 ,10598.9 ,59.9,59.9,59.9
XS GIS Cut Line= 6
     1769204.189      511365.066     1769240.647      511312.983
     1769254.536      511290.413     1769278.842      511130.691
     1769310.092      510932.775     1769268.425      510839.025
#Sta/Elev= 30
       0   643.1    36.3  643.09    54.5  642.86    81.2  642.06    90.1  641.59
    99.6  639.65   109.1  636.46   111.4  635.91   118.6  634.18   128.1  633.88
   137.6  635.84   147.1  638.94   156.6  639.91   166.1  639.26   175.6  639.17
   185.1  639.37   204.1  639.61   223.1   640.1   251.6  640.58   299.3  641.13
     328   641.3     347   641.2   356.6  640.89   366.1   640.7   385.2  641.06
   394.8  641.14     452  641.32     480  641.82     508  642.62   554.6   643.8
#Mann= 3 , 0 , 0
       0     .07       0   111.4    .045       0   128.1     .06       0
Bank Sta=111.4,128.1
XS Rating Curve= 0 ,0
Exp/Cntr=0.3,0.1

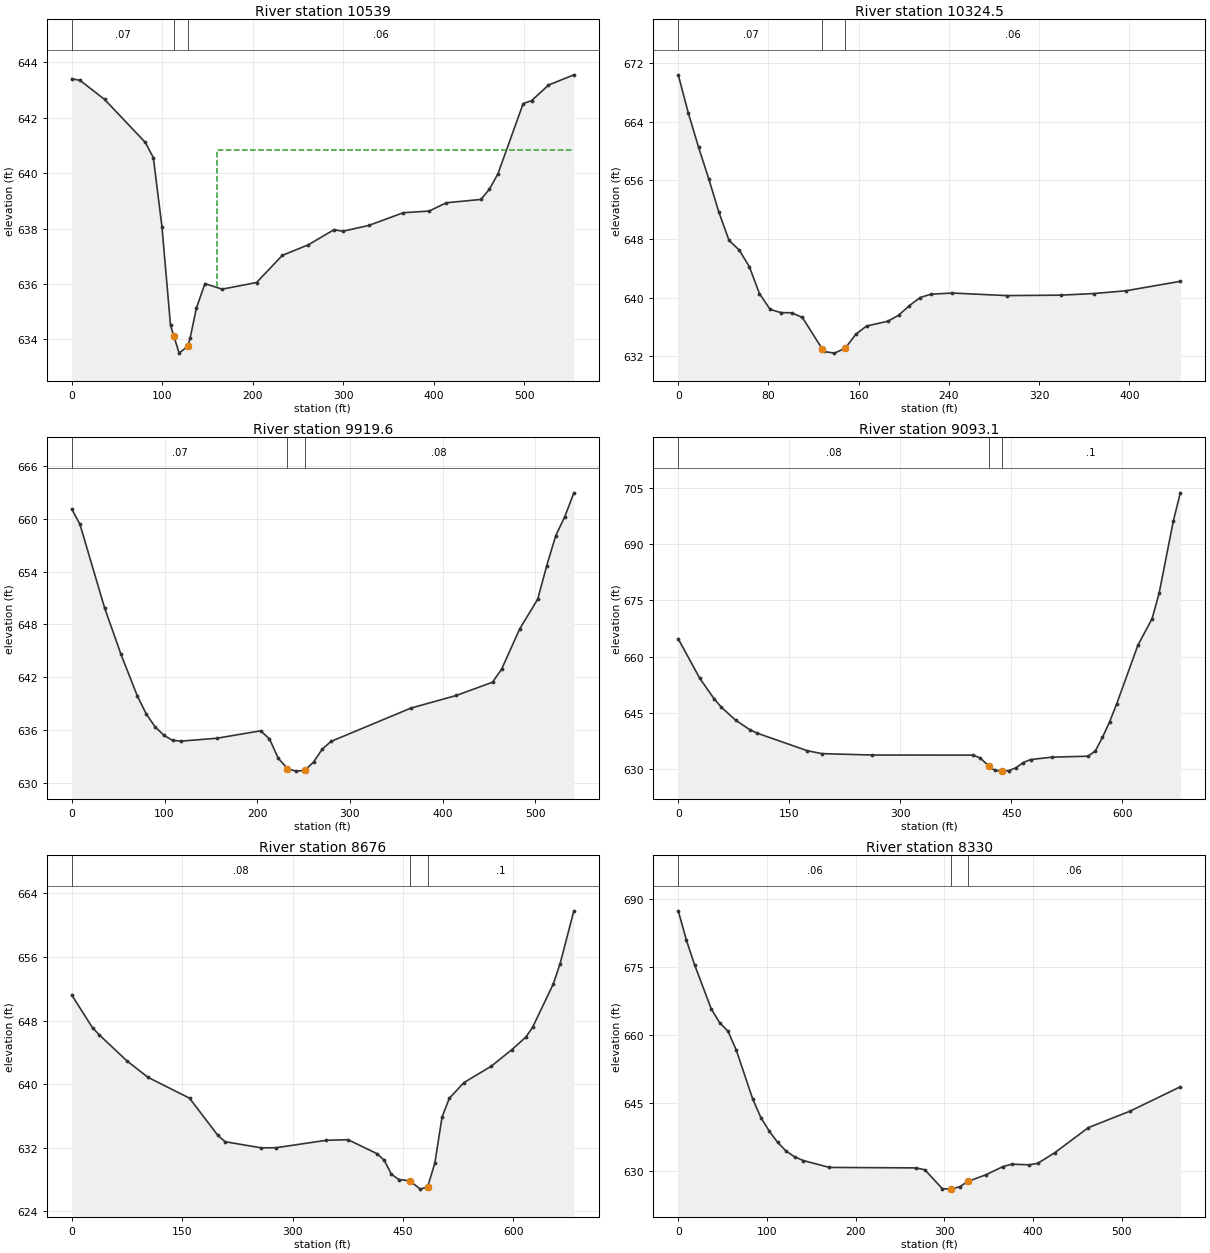
Type RM Length L Ch R = 1 ,10539   ,226.6,214.5,201.9
XS GIS Cut Line= 6
     1769263.217      511373.747     1769299.675      511321.663
     1769313.564      511299.094      1769337.87      511139.372
      1769369.12      510941.455     1769327.453      510847.705
#Sta/Elev= 30
       0  643.41     9.1  643.35    36.3  642.66    81.2  641.11    90.1  640.56
    99.6  638.07   109.1   634.5   112.8  634.11   118.6   633.5   128.1  633.75
  130.74  634.04   137.6  635.12   147.1  636.01   166.1  635.81   204.1  636.05
   232.6  637.03   261.2  637.41   289.8  637.96   299.3   637.9     328  638.11
   366.1  638.57   394.8  638.63   413.8  638.93     452  639.05   461.3  639.42
   470.7  639.97   498.6  642.51     508  642.62   526.6  643.18   554.6  643.55
#Mann= 3 , 0 , 0
       0     .07       0   112.8    .045       0   128.1     .06       0
#XS Ineff= 2 , 0
                           160.2          640.84
Permanent Ineff=
       F       F
Bank Sta=112.8,128.1
XS Rating Curve= 0 ,0
Exp/Cntr=0.3,0.1

Type RM Length L Ch R = 1 ,10324.5 ,397.2,404.9,412.8
XS GIS Cut Line= 4
     1769558.356       511332.08     1769539.259      511262.636
     1769481.967      511122.011     1769448.981      510903.261
#Sta/Elev= 30
       0  670.43       9  665.18      18  660.55      27  656.25      36  651.68
      45  647.82      54   646.5      63  644.24      72  640.54    81.5  638.38
      91  637.95   100.5  637.92     110   637.3   127.8  632.95     129  632.64
   138.5  632.41     148  633.07   157.4  634.98   166.9  636.11   185.9  636.77
   195.4  637.59   204.9   638.9   214.4     640   223.9  640.46   243.1  640.62
   291.2  640.27   339.3  640.33   368.2  640.55     397  640.93   445.1  642.22
#Mann= 3 , 0 , 0
       0     .07       0   127.8    .045       0     148     .06       0
Bank Sta=127.8,148
XS Rating Curve= 0 ,0
Exp/Cntr=0.3,0.1

Type RM Length L Ch R = 1 ,9919.6  ,815.2,826.5,836
XS GIS Cut Line= 4
     1769905.578      511295.622     1769891.689      511226.177
     1769881.272      510960.552     1769855.231      510757.427
#Sta/Elev= 30
       0  661.12     8.8  659.39    35.4  649.88    53.1  644.58    70.8  639.83
    80.3  637.81    89.8  636.35    99.3  635.38   108.8  634.79   118.3  634.72
   156.3  635.04   203.7  635.89   213.2  634.96   222.7  632.76   232.6  631.59
   241.7   631.3   251.2  631.39   260.7  632.33   270.2  633.82   279.7  634.69
   365.9  638.48   414.7  639.91   453.7  641.42   463.4  642.88   482.9  647.46
   502.4  650.86   512.2  654.69   521.9   658.1   531.7  660.27   541.4  662.97
#Mann= 3 , 0 , 0
       0     .07       0   232.6    .045       0   251.2     .08       0
Bank Sta=232.6,251.2
XS Rating Curve= 0 ,0
Exp/Cntr=0.3,0.1

Type RM Length L Ch R = 1 ,9093.1  ,414.5,417.1,413.9
XS GIS Cut Line= 4
      1770159.05      511356.386     1770245.856      511240.066
     1770435.092      510866.802     1770442.036      510752.219
#Sta/Elev= 30
       0  664.74      29  654.23    48.4  648.74    58.1  646.51    77.4  643.03
    96.8  640.46   106.4  639.56   174.3  634.86   193.8  634.08   261.9   633.7
   398.2  633.68   407.9  632.93     420   630.7   427.4  629.64   437.1   629.4
   446.8  629.54   456.6  630.33   466.3   631.7     476  632.49   505.2  633.14
   553.9  633.39   563.6   634.8   573.2  638.42   582.8  642.55   592.3  647.29
     621  662.99   640.2   670.1   649.7  676.85   668.9  696.16   678.4  703.74
#Mann= 3 , 0 , 0
       0     .08       0     420    .045       0   437.1      .1       0
Bank Sta=420,437.1
XS Rating Curve= 0 ,0
Exp/Cntr=0.3,0.1

Type RM Length L Ch R = 1 ,8676    ,348.6,346,343.7
XS GIS Cut Line= 4
     1770575.717        511448.4     1770579.189       511269.58
     1770723.286      510946.663     1770763.217      510802.566
#Sta/Elev= 30
       0  651.21    28.2  647.09    37.6  646.18    75.3   642.9   103.6  640.86
     160  638.24   198.5  633.56   208.3  632.77   257.4     632   277.1  632.01
   345.8  632.95   375.3  633.02   414.6  631.27   424.4  630.44   434.2  628.68
   444.1  628.02   458.9  627.86   473.5  626.81   483.4  627.09   493.2  630.09
     503  635.88   512.8  638.22   532.5  640.19   569.8  642.26   597.9  644.35
   616.6   645.9   625.9  647.14     654  652.58   663.3  655.14     682  661.79
#Mann= 3 , 0 , 0
       0     .08       0   458.9    .045       0   483.4      .1       0
Bank Sta=458.9,483.4
XS Rating Curve= 0 ,0
Exp/Cntr=0.3,0.1

Type RM Length L Ch R = 1 ,8330    ,311,322,333
XS GIS Cut Line= 4
     1770867.384      511469.233     1770907.314       511354.65
     1771016.689       511082.08     1771047.939      510934.511
#Sta/Elev= 30
       0  687.41     9.3  680.87    18.7  675.34    37.3   665.7    46.7  662.68
      56  660.82    65.3   656.7      84  645.79    93.3  641.66   102.7  638.69
     112  636.25   121.3  634.36   131.1  633.05   140.9  632.22   170.3   630.7
   268.2  630.59     278  630.17   297.6  626.01   307.4   625.9   317.1  626.42
   326.9  627.63   346.5  629.05   366.1  630.89   375.9  631.42   395.5  631.27
   405.2   631.6   424.5  633.96   462.2  639.49   509.3  643.14   565.9  648.52
#Mann= 3 , 0 , 0
       0     .06       0   307.4    .045       0   326.9     .06       0
Bank Sta=307.4,326.9
XS Rating Curve= 0 ,0
Exp/Cntr=0.3,0.1

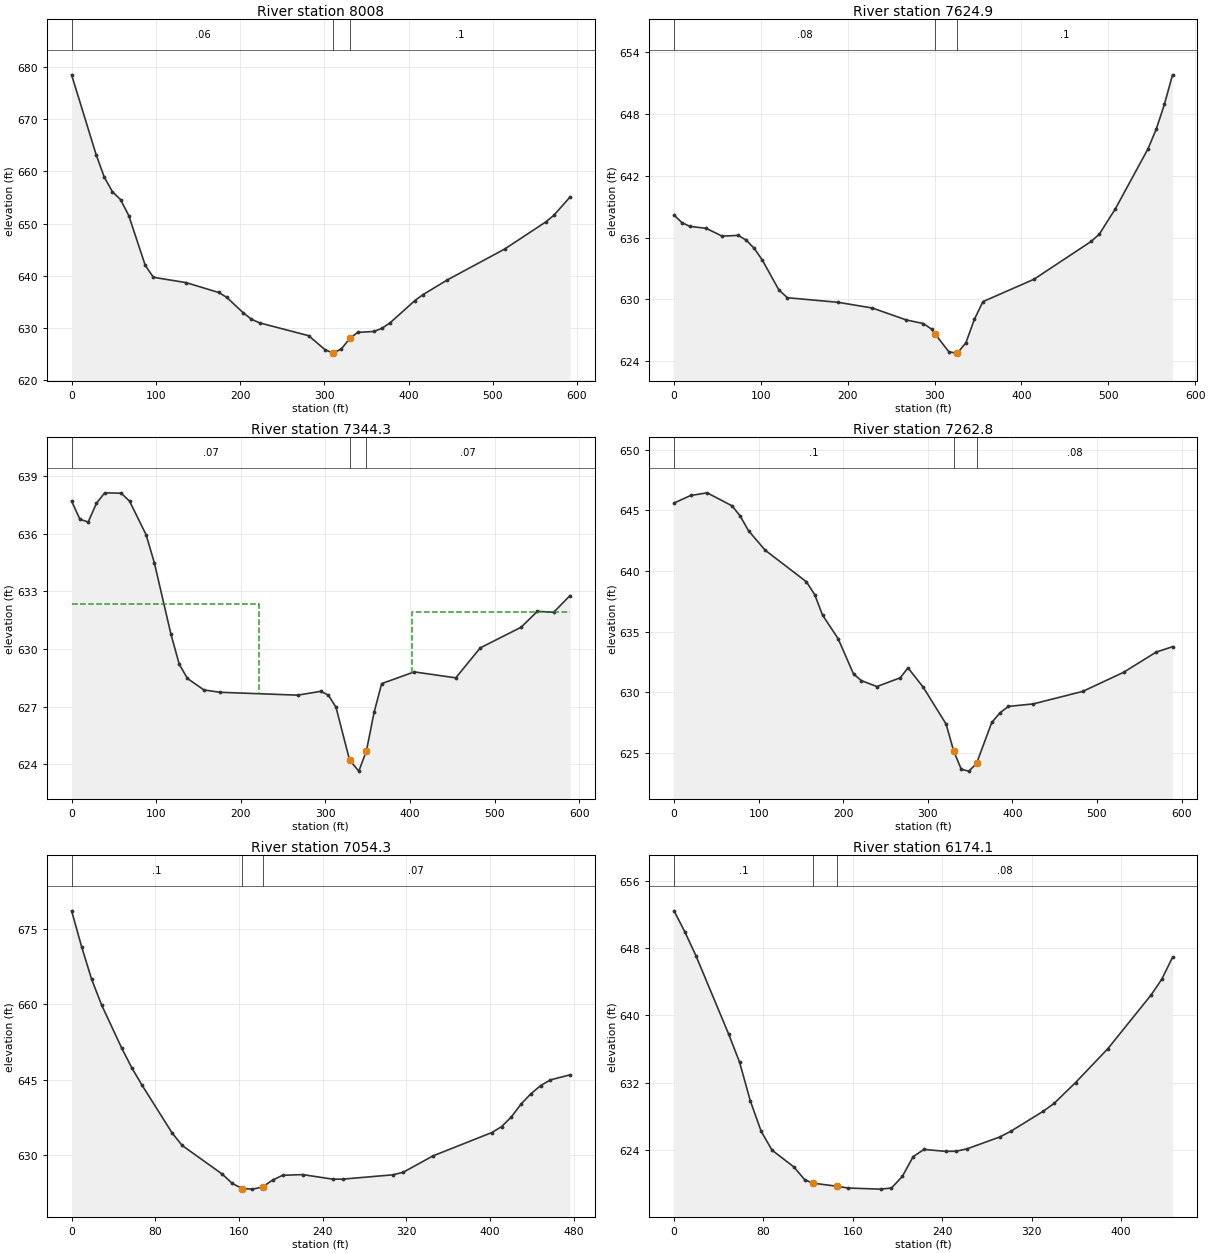
Type RM Length L Ch R = 1 ,8008    ,373,383.1,393
XS GIS Cut Line= 4
     1771075.717      511536.941       1771190.3      511368.538
     1771325.717      511243.538       1771440.3      511075.136
#Sta/Elev= 30
       0  678.45    29.1   663.2    38.8  658.88    48.5  656.08    58.2  654.57
    67.9  651.52    87.3  642.07      97  639.73   135.8  638.71   174.6  636.82
   184.3  635.88   203.7  632.94   213.4  631.72   223.1  631.01   281.3  628.56
   300.7   625.9   310.4  625.22   320.1  626.01   330.6  628.08   339.5  629.18
   358.9  629.37   368.6  629.98   378.3  631.05   407.4  635.26   417.1   636.4
   446.2  639.24   514.1  645.13   562.6  650.28   572.3  651.55   591.7  655.08
#Mann= 3 , 0 , 0
       0     .06       0   310.4    .045       0   330.6      .1       0
Bank Sta=310.4,330.6
XS Rating Curve= 0 ,0
Exp/Cntr=0.3,0.1

Type RM Length L Ch R = 1 ,7624.9  ,281.5,280.6,279.6
XS GIS Cut Line= 4
      1771306.62      511556.038     1771396.897      511491.802
     1771683.356      511391.108     1771797.939      511279.997
#Sta/Elev= 30
       0  638.18     9.2  637.44    18.5  637.08    36.9   636.9    55.4  636.14
    73.9  636.21    83.1  635.75    92.3  634.95   101.6  633.82   120.6  630.93
   130.4  630.16   189.2  629.71   228.3  629.16   267.5     628   287.1  627.65
   296.9  627.09   300.5  626.65   316.5   624.9   326.3  624.78   336.1  625.79
   345.9  628.08   355.7  629.78   414.4  631.95   480.2  635.62   489.6  636.32
   508.3  638.81   545.9  644.64   555.3  646.54   564.7  648.95     574   651.8
#Mann= 3 , 0 , 0
       0     .08       0   300.5    .045       0   326.3      .1       0
Bank Sta=300.5,326.3
XS Rating Curve= 0 ,0
Exp/Cntr=0.3,0.1

Type RM Length L Ch R = 1 ,7344.3  ,81.5,81.5,81.5
XS GIS Cut Line= 6
     1771336.134      511592.497     1771481.967      511672.358
     1771582.661      511717.497     1771674.675      511681.038
     1771731.967      511627.219     1771858.703      511580.344
#Sta/Elev= 30
       0  637.69     9.8  636.75    19.6   636.6    29.3  637.57    39.1  638.12
    58.7   638.1    68.5  637.69      88  635.95    97.8  634.49   117.4  630.78
   127.2  629.22   136.9  628.47   156.5  627.87   175.5  627.75   267.4   627.6
   294.6   627.8   303.6   627.6   312.6  626.97   328.7  624.22   339.6  623.65
   348.6  624.71   357.6   626.7   366.6   628.2   405.1  628.81   454.2   628.5
   483.2  630.06   531.4  631.13   550.7  631.96     570  631.91   589.3  632.78
#Mann= 3 , 0 , 0
       0     .07       0   328.7    .045       0   348.6     .07       0
#XS Ineff= 2 , 0
          221.39  632.32  402.41          631.93
Permanent Ineff=
       F       F
Bank Sta=328.7,348.6
XS Rating Curve= 0 ,0
Exp/Cntr=0.3,0.1

Type RM Length L Ch R = 1 ,7262.8  ,213,208.5,203.9
XS GIS Cut Line= 6
     1771356.967      511670.622       1771502.8      511750.483
     1771603.495      511795.622     1771695.509      511759.163
       1771752.8      511705.344     1771879.536      511658.469
#Sta/Elev= 30
       0  645.61    19.6  646.23    39.1  646.45    68.5  645.38    78.2  644.54
      88  643.33   107.6  641.73   156.5  639.12   166.3  638.06   175.5  636.38
   193.9  634.44   212.2  631.52   221.4  630.98   239.8  630.49   267.4  631.21
   276.6  632.03   294.6  630.43   321.6   627.4   330.6  625.17   339.6  623.67
   348.6  623.52   357.6  624.16   375.6  627.53   385.4  628.33   395.2  628.85
   424.7  629.06   483.2  630.09   531.4  631.66     570  633.33   589.3  633.77
#Mann= 3 , 0 , 0
       0      .1       0   330.6    .045       0   357.6     .08       0
Bank Sta=330.6,357.6
XS Rating Curve= 0 ,0
Exp/Cntr=0.3,0.1

Type RM Length L Ch R = 1 ,7054.3  ,874,880.2,950.1
XS GIS Cut Line= 3
     1771655.578        512010.9     1771933.356      511821.663
      1772025.37      511715.761
#Sta/Elev= 30
       0  678.56     9.6  671.42    19.2  664.92    28.8  659.78      48  651.22
    57.6  647.31    67.2  643.93      96  634.41   105.6  631.91     144   626.2
   153.6  624.34   163.2  623.32   172.9  623.21   182.5  623.63   192.1  625.01
   201.7  625.96   220.9   626.1   249.7  625.19   259.3   625.2   307.3  626.06
   316.9  626.56   345.5  629.83   401.6  634.46   410.9  635.63   420.3  637.56
   429.6  640.13     439  642.18   448.4  643.82   457.7  644.94   476.4  645.94
#Mann= 3 , 0 , 0
       0      .1       0   163.2    .045       0   182.5     .07       0
Bank Sta=163.2,182.5
XS Rating Curve= 0 ,0
Exp/Cntr=0.3,0.1

Type RM Length L Ch R = 1 ,6174.1  ,330.8,320.2,278.1
XS GIS Cut Line= 4
     1772054.667      512541.499      1772104.58      512494.841
     1772280.361      512313.634     1772343.295      512205.127
#Sta/Elev= 30
       0  652.41     9.8  649.87    19.5  647.11    48.8  637.81    58.6  634.47
    68.3  629.85      78  626.25    87.7  624.02   107.2  622.04   116.9  620.52
   124.2  620.11     146  619.74   155.7  619.53   184.8   619.4   194.6  619.53
   204.3   620.9     214  623.25   223.7  624.11   243.1  623.88   252.8   623.9
   262.5  624.19   291.6  625.59   301.4  626.26   330.4  628.63   340.1  629.56
   359.4  632.04   388.3  636.06   426.9  642.41   436.6   644.3   446.2   646.9
#Mann= 3 , 0 , 0
       0      .1       0   124.2    .045       0     146     .08       0
Bank Sta=124.2,146
XS Rating Curve= 0 ,0
Exp/Cntr=0.3,0.1