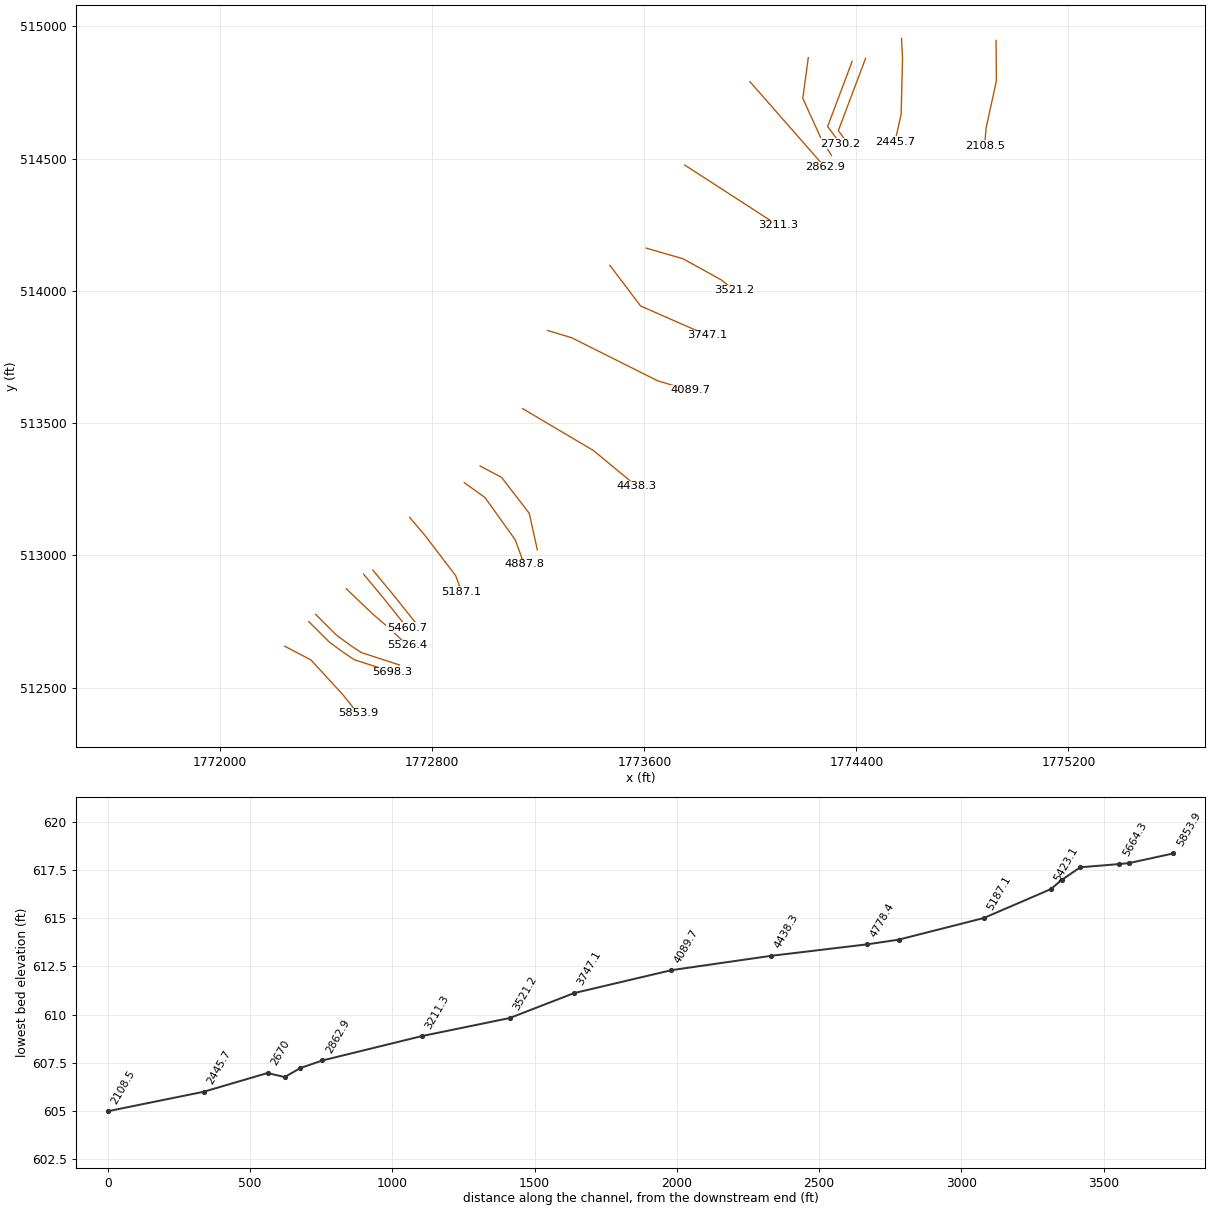
HEC-RAS study TWOMILECK.prj: TWOMILECK

--- TWOMILECK.g01 (geometry) --- (continued)

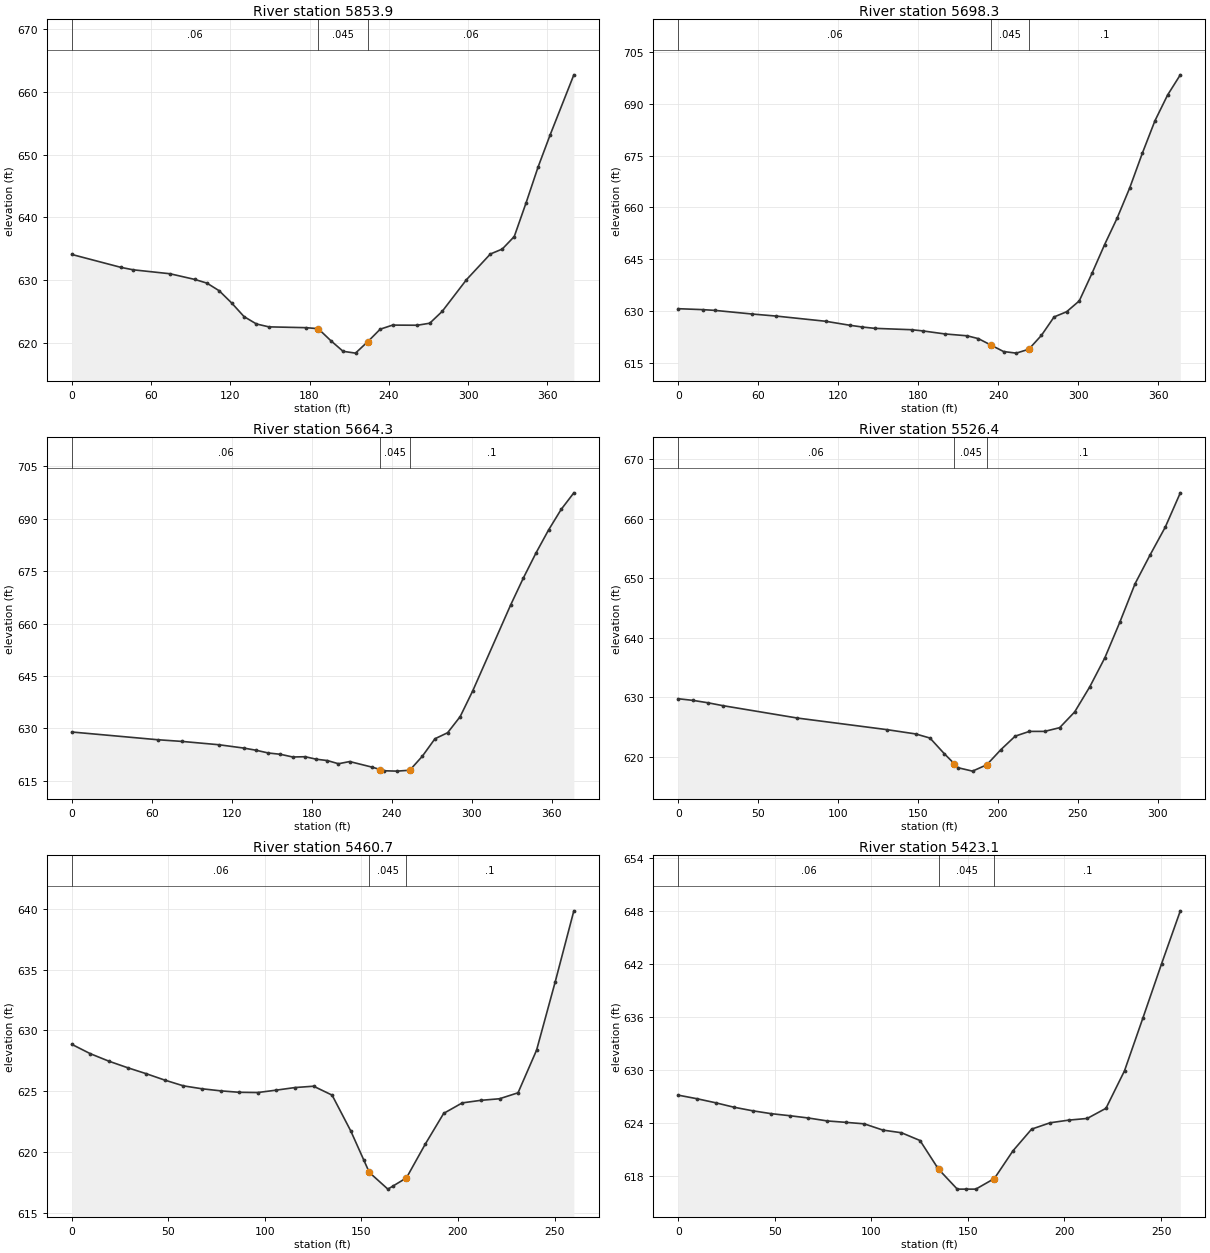
Type RM Length L Ch R = 1 ,5853.9  ,143.4,155.6,167.7
XS GIS Cut Line= 4
     1772243.469      512656.516      1772342.21      512604.433
     1772462.653      512473.139     1772519.076       512402.61
#Sta/Elev= 30
       0  634.09    37.2  632.03    46.5  631.64    74.4  631.01      93  630.11
   102.3  629.52   111.6   628.3     121  626.36   130.4  624.18   139.8     623
   149.2  622.54   177.3  622.41   186.6  622.25     196  620.36   205.4  618.64
   214.8  618.35   224.2   620.2   233.5  622.17   242.9  622.82   261.7   622.8
     271  623.12   280.4     625   298.8  630.06   316.9  634.16   325.9  634.95
     335  636.95     344  642.36     353  648.02   362.1  653.13   380.1  662.74
#Mann= 3 , 0 , 0
       0     .06       0   186.6    .045       0   224.2     .06       0
Bank Sta=186.6,224.2
XS Rating Curve= 0 ,0
Exp/Cntr=0.3,0.1

Type RM Length L Ch R = 1 ,5698.3  ,36.4,34,34
XS GIS Cut Line= 5
     1772333.963      512749.615     1772412.088       512671.49
     1772464.172      512633.295     1772505.838      512605.518
     1772649.936      512558.643
#Sta/Elev= 30
       0   630.7    18.4  630.43    27.6  630.21    55.2  629.17    73.7  628.56
   110.5  627.07   128.9   625.9   138.2   625.4   147.4  625.02   175.1  624.62
   183.4  624.28   200.1   623.4   216.8  622.86   225.2  622.04   234.6  620.18
   244.1  618.31   253.6  617.85     263  618.97   272.5  622.99     282  628.32
   291.4  629.82   300.9  632.96   310.4  640.91   319.9  649.24   329.3  656.91
   338.8   665.7   348.3  675.77   357.7  685.09   367.2  692.54   376.7  698.35
#Mann= 3 , 0 , 0
       0     .06       0   234.6    .045       0     263      .1       0
Bank Sta=234.6,263
XS Rating Curve= 0 ,0
Exp/Cntr=0.3,0.1

Type RM Length L Ch R = 1 ,5664.3  ,144.4,137.9,129
XS GIS Cut Line= 5
     1772360.005      512776.742      1772438.13      512698.617
     1772490.213      512660.422      1772531.88      512632.644
     1772675.977      512585.769
#Sta/Elev= 30
       0  628.99    64.4  626.78    82.9  626.29   110.5  625.34   128.9   624.4
   138.2  623.78   147.4  622.99   156.6  622.61   165.8  621.84   175.1  621.92
   183.4  621.21   191.8  620.82   200.1  619.91   208.5  620.54   225.2  618.95
   231.4  618.26   234.6   617.9   244.1   617.8   253.6  618.06     263  622.05
   272.5  627.06     282  628.78   291.4  633.38   300.9  640.81   329.3  665.33
   338.8  673.01   348.3  680.18   357.7  686.74   367.2  692.65   376.7  697.38
#Mann= 3 , 0 , 0
       0     .06       0   231.4    .045       0   253.6      .1       0
Bank Sta=231.4,253.6
XS Rating Curve= 0 ,0
Exp/Cntr=0.3,0.1

Type RM Length L Ch R = 1 ,5526.4  ,70.5,65.7,60.9
XS GIS Cut Line= 4
     1772475.674       512873.53     1772576.585      512776.959
     1772637.349      512724.875     1772705.708      512659.771
#Sta/Elev= 26
       0  629.78     9.3   629.5    18.6   629.1    27.9  628.62    74.5  626.54
   130.4   624.6   148.6  623.87   157.5  623.18   166.4  620.57   172.7  618.87
   175.2  618.19   184.1  617.63     193  618.69   201.9  621.25   210.8   623.5
   219.7   624.3   229.2   624.3   238.6  624.92     248  627.56   257.5   631.8
   266.9  636.66   276.4  642.72   285.8  649.09   295.2  653.92   304.7  658.59
   314.1  664.34
#Mann= 3 , 0 , 0
       0     .06       0   172.7    .045       0     193      .1       0
Bank Sta=172.7,193
XS Rating Curve= 0 ,0
Exp/Cntr=0.3,0.1

Type RM Length L Ch R = 1 ,5460.7  ,36.9,37.6,37.9
XS GIS Cut Line= 3
     1772540.778      512928.868     1772614.562      512839.893
     1772704.623      512727.045
#Sta/Elev= 30
       0  628.86     9.6  628.09    19.3  627.47    28.9  626.94    38.5  626.45
    48.2  625.92    57.8  625.45    67.4  625.21    77.1  625.04    86.7  624.92
    96.3   624.9     106   625.1   115.6  625.31   125.2  625.42   134.8  624.69
   144.5  621.74   151.3  619.33   154.1  618.34   163.7  616.97   166.3  617.22
   173.3  617.89     183  620.65   192.6  623.19   202.2  624.05   211.8  624.26
   221.5  624.39   231.1  624.88   240.7  628.38   250.3  633.96     260  639.82
#Mann= 3 , 0 , 0
       0     .06       0   154.1    .045       0   173.3      .1       0
Bank Sta=154.1,173.3
XS Rating Curve= 0 ,0
Exp/Cntr=0.3,0.1

Type RM Length L Ch R = 1 ,5423.1  ,236.6,236,235.4
XS GIS Cut Line= 3
       1772575.5      512944.059     1772649.285      512855.084
     1772739.345      512742.236
#Sta/Elev= 30
       0  627.15     9.6  626.75    19.3  626.29    28.9  625.78    38.5  625.38
    48.2  625.05    57.8  624.82    67.4  624.56    77.1  624.23    86.7  624.07
    96.3   623.9     106  623.19   115.6  622.89   125.2  622.01   133.9  619.06
   134.8  618.76   144.5   616.5   148.9   616.5   154.1   616.5   163.7   617.7
   173.3  620.83     183   623.3   192.6  624.02   202.2  624.32   211.8  624.51
   221.5  625.66   231.1  629.91   240.7  635.94   250.3  642.04     260  648.04
#Mann= 3 , 0 , 0
       0     .06       0   134.8    .045       0   163.7      .1       0
Bank Sta=134.8,163.7
XS Rating Curve= 0 ,0
Exp/Cntr=0.3,0.1

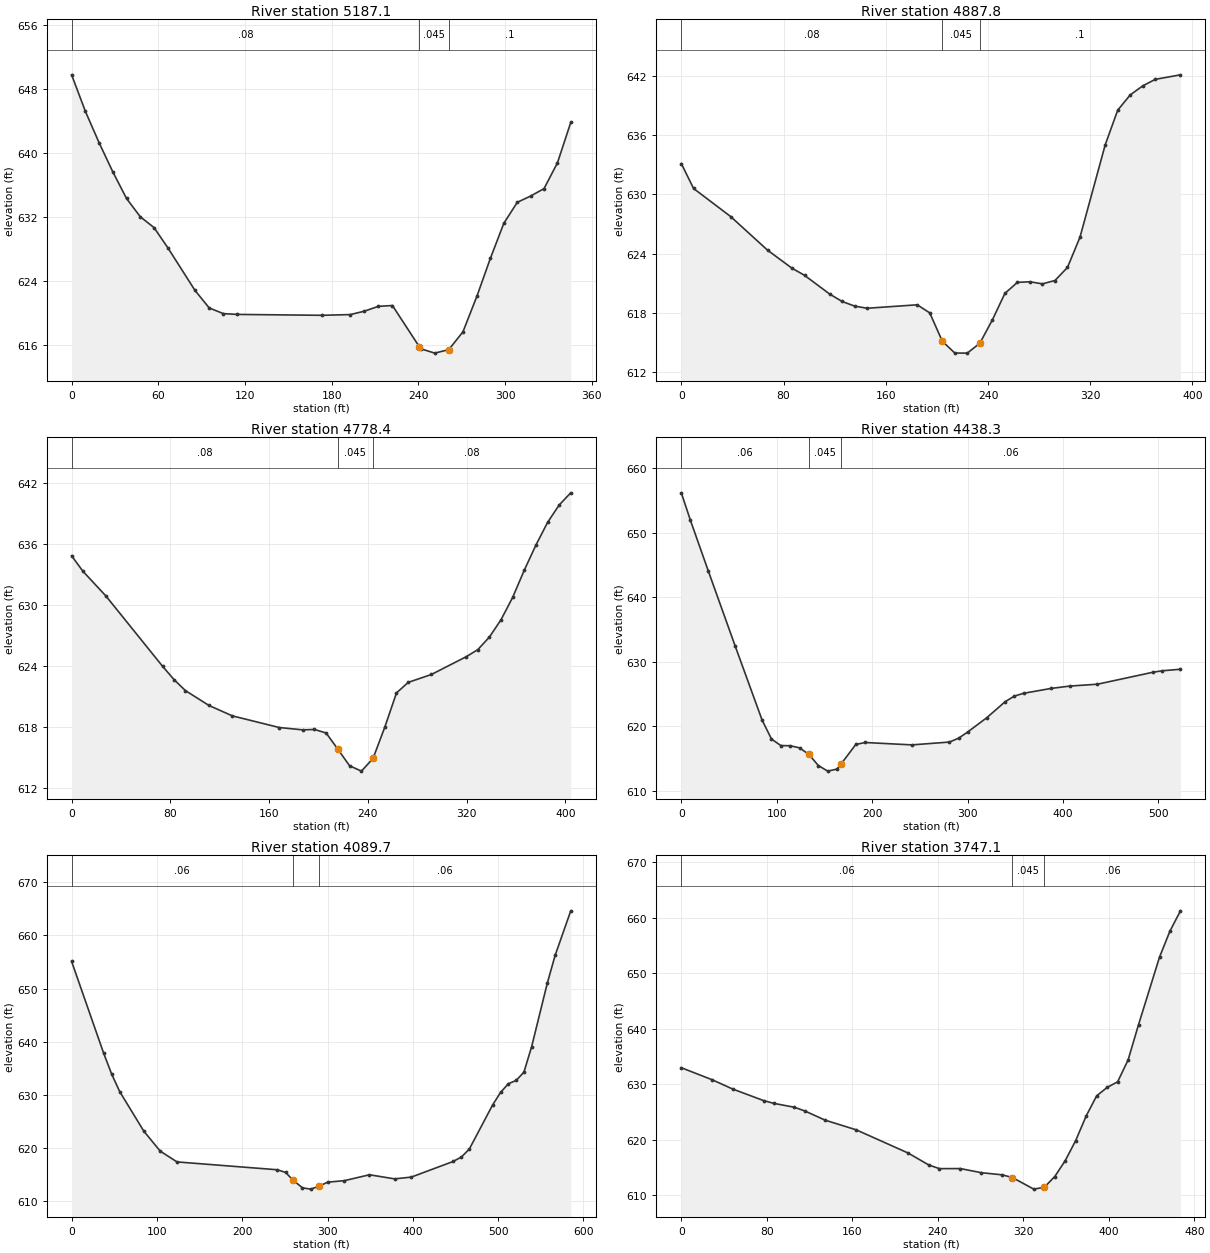
Type RM Length L Ch R = 1 ,5187.1  ,297.9,299.3,300.2
XS GIS Cut Line= 4
     1772714.389      513143.712     1772769.727      513078.608
        1772888.      512923.443     1772910.786      512862.679
#Sta/Elev= 30
       0  649.73     9.5  645.18      19  641.26    28.5  637.62      38   634.3
    47.5  632.02      57  630.67    66.5  628.17    85.4  622.82    95.2  620.64
     105  619.93   114.7  619.83   173.2  619.72   192.8  619.81   202.5  620.23
   212.3  620.84     222  620.94   240.6   615.8   241.5  615.55   251.3     615
     261  615.44   270.8  617.66   280.6  622.17   289.8  626.84   299.1  631.21
   308.4  633.82   317.6   634.6   326.9  635.53   336.2  638.75   345.4  643.79
#Mann= 3 , 0 , 0
       0     .08       0   240.6    .045       0     261      .1       0
Bank Sta=240.6,261
XS Rating Curve= 0 ,0
Exp/Cntr=0.3,0.1

Type RM Length L Ch R = 1 ,4887.8  ,110.8,109.4,108.5
XS GIS Cut Line= 4
     1772920.552      513275.005     1772998.677      513218.582
     1773112.609      513059.077     1773146.246      512966.846
#Sta/Elev= 30
       0  633.14     9.6  630.61    38.6  627.76    67.5  624.34    86.7   622.5
    96.4  621.79     116  619.89   125.8  619.13   135.6  618.66   145.4  618.44
   184.6  618.79   194.4  617.97   204.2   615.1     214  613.89   223.8  613.88
   233.6  614.89   243.4  617.25   253.2  619.95     263  621.07   272.8  621.13
   282.6  620.92   292.4  621.26   302.2  622.59     312  625.67   331.7  635.04
   341.5  638.57   351.3  640.12   361.1  641.04   370.9   641.7   390.6  642.16
#Mann= 3 , 0 , 0
       0     .08       0   204.2    .045       0   233.6      .1       0
Bank Sta=204.2,233.6
XS Rating Curve= 0 ,0
Exp/Cntr=0.3,0.1

Type RM Length L Ch R = 1 ,4778.4  ,329.8,340.1,350.2
XS GIS Cut Line= 4
     1772980.231      513337.939     1773061.611      513294.537
     1773165.778      513158.903      1773196.16      513021.099
#Sta/Elev= 30
       0  634.87     9.2  633.34    27.7  630.92    73.8  623.96      83  622.66
    92.2  621.58   111.2  620.12   130.2  619.09   168.2  617.94   187.2  617.71
   196.7  617.75   206.2   617.4   215.6  615.82   225.2  614.17   234.8  613.64
   244.2  614.89   253.8     618   263.2  621.35   272.7  622.39   291.5  623.17
   319.7  624.92   329.1  625.62   338.5  626.86   347.9  628.57   357.3  630.76
   366.7  633.44   376.1  635.91   385.6  638.16     395  639.88   404.4  641.08
#Mann= 3 , 0 , 0
       0     .08       0   215.6    .045       0   244.2     .08       0
Bank Sta=215.6,244.2
XS Rating Curve= 0 ,0
Exp/Cntr=0.3,0.1

Type RM Length L Ch R = 1 ,4438.3  ,346.4,348.6,350.7
XS GIS Cut Line= 4
     1773140.821      513554.953     1773213.521      513511.551
     1773407.748      513396.533     1773571.594        513260.9
#Sta/Elev= 30
       0   656.2     9.4     652    28.2  644.11    56.4  632.46    84.7  620.94
    94.5  618.02   104.3     617   114.1  616.98   123.9  616.65   133.7  615.63
   143.6  613.91   153.4  613.04   163.2  613.36   167.3  614.12   182.8  617.17
   192.6  617.48   241.7  617.11     281  617.55   290.8  618.16   300.6  619.16
   320.1  621.32   339.4  623.81   349.1  624.68   358.7  625.11   387.7  625.87
   407.1  626.23   436.1  626.52   494.1  628.37   503.8   628.6   523.1  628.84
#Mann= 3 , 0 , 0
       0     .06       0   133.7    .045       0   167.3     .06       0
Bank Sta=133.7,167.3
XS Rating Curve= 0 ,0
Exp/Cntr=0.3,0.1

Type RM Length L Ch R = 1 ,4089.7  ,338.8,342.6,346.1
XS GIS Cut Line= 4
     1773235.222      513850.092     1773325.283      513822.966
     1773649.719      513660.205     1773772.332      513623.313
#Sta/Elev= 30
       0  655.11    37.6  637.84      47  633.91    56.4  630.63    84.6  623.21
   103.9  619.44   123.5  617.42   241.2  615.94     251  615.43   259.2  614.03
   270.6  612.54   280.4   612.3   290.3  612.87   300.1  613.61   319.7  613.89
   349.1     615   378.6  614.23   398.2  614.56   447.2   617.5     457  618.35
   466.2  619.84   493.6  628.16   502.8  630.48   511.9  632.12     521  632.73
   530.2   634.3   539.3  639.12   557.6  651.04   566.8  656.27   585.1  664.64
#Mann= 3 , 0 , 0
       0     .06       0   259.2    .045       0   290.3     .06       0
Bank Sta=259.2,290.3
XS Rating Curve= 0 ,0
Exp/Cntr=0.3,0.1

Type RM Length L Ch R = 1 ,3747.1  ,228.2,225.9,222.5
XS GIS Cut Line= 3
     1773469.814       514096.62       1773585.7      513942.974
     1773837.002      513832.297
#Sta/Elev= 30
       0  632.97    28.9   630.8    48.1  629.13      77  627.05    86.6  626.55
   105.8  625.85   115.5  625.19   134.7  623.52   163.6  621.79   212.1  617.62
   231.7  615.44   241.5   614.8   261.1  614.81   280.7  614.07   300.3  613.68
   309.7   613.2   329.8  611.11   339.6  611.44   349.4  613.38   359.2  616.24
     369  619.86   378.8  624.29   388.6  627.91   398.4  629.42   408.2  630.43
     418  634.36   427.8  640.74   447.4  652.88   457.2  657.59     467  661.22
#Mann= 3 , 0 , 0
       0     .06       0   309.7    .045       0   339.6     .06       0
Bank Sta=309.7,339.6
XS Rating Curve= 0 ,0
Exp/Cntr=0.3,0.1

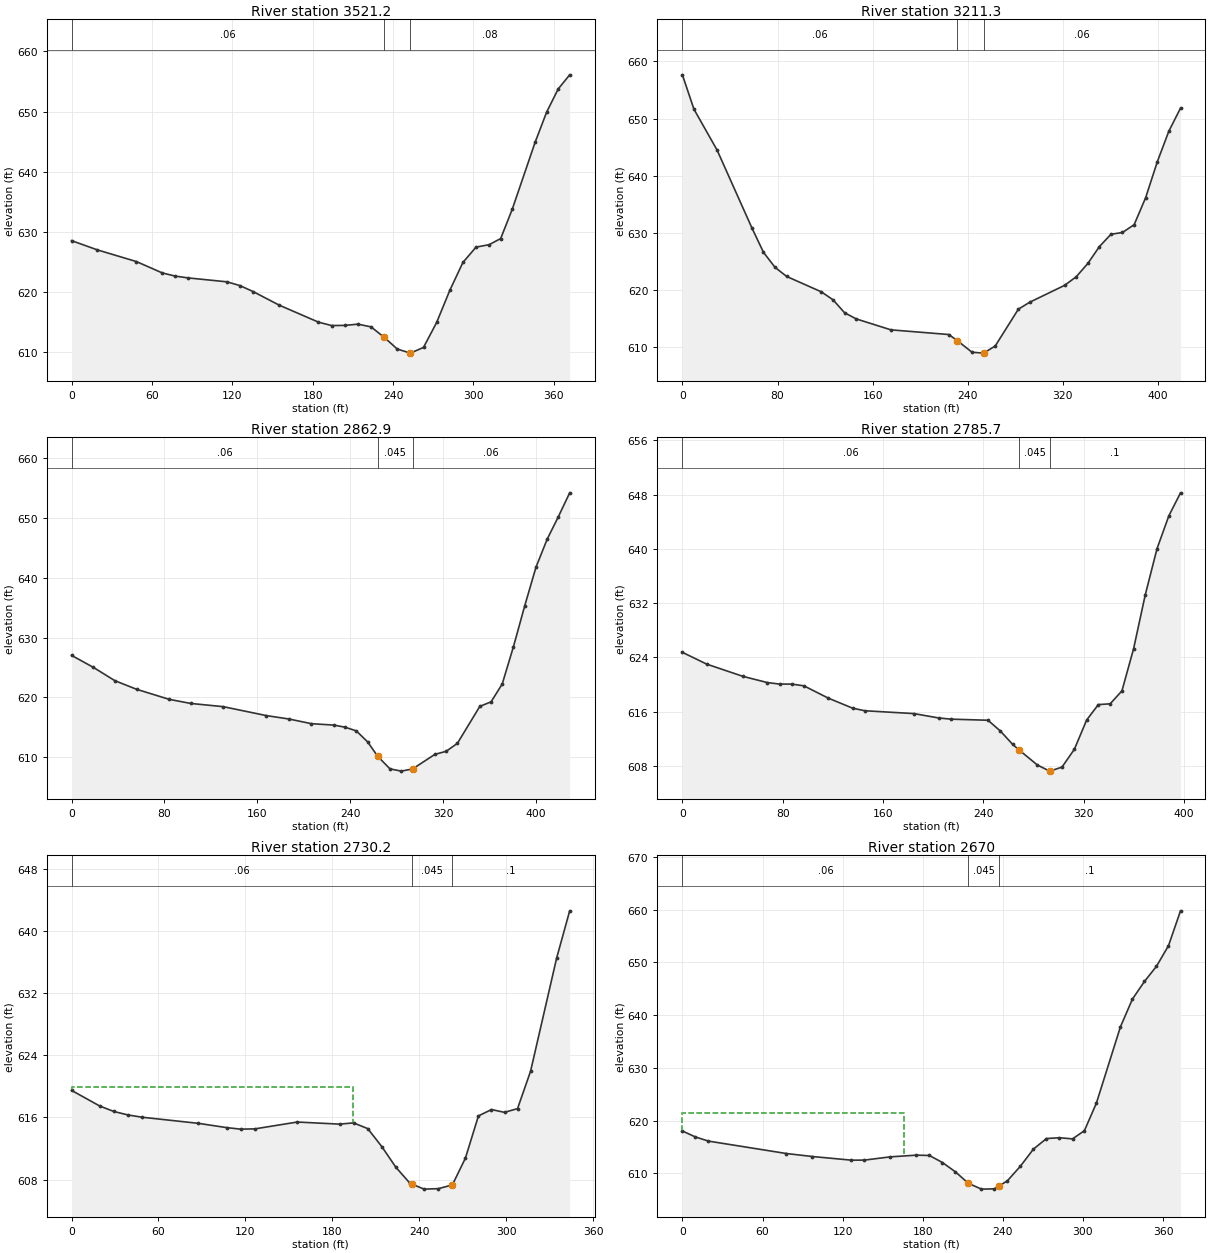
Type RM Length L Ch R = 1 ,3521.2  ,311.4,309.9,308.3
XS GIS Cut Line= 4
     1773606.533      514161.724     1773745.856       514121.36
     1773891.689       514040.63     1773937.262      514001.568
#Sta/Elev= 30
       0  628.53    19.3  626.99    48.4  625.05    67.7  623.16    77.4  622.63
      87  622.33     116  621.68   125.7  621.05   135.4  620.07   154.9  617.81
   184.3  614.97   194.1  614.41   203.9  614.43   213.7  614.64   223.5  614.19
   233.3  612.46   243.1   610.5   252.9  609.82   262.7  610.77   272.5  614.92
   282.3  620.25   292.1   624.9   301.9  627.45   311.7  627.86   320.3  628.88
   328.9  633.73     346  644.89   354.6   649.9   363.2  653.75   371.8  656.11
#Mann= 3 , 0 , 0
       0     .06       0   233.3    .045       0   252.9     .08       0
Bank Sta=233.3,252.9
XS Rating Curve= 0 ,0
Exp/Cntr=0.3,0.1

Type RM Length L Ch R = 1 ,3211.3  ,354.3,348.5,341.6
XS GIS Cut Line= 2
     1773752.366      514475.526     1774103.929      514247.662
#Sta/Elev= 30
       0  657.66     9.7  651.64    29.2  644.46    58.5  630.81    68.2  626.55
    77.9  623.92    87.7  622.32   116.9  619.62   126.7  618.23   136.4  615.96
   146.2  614.88   175.4  612.96   224.1  612.14   231.3  611.06   243.6  609.04
   253.3  608.88   263.1  610.12   282.6  616.58   292.3  617.82   321.5  620.76
   331.3  622.27     341  624.59   350.8  627.56   360.5  629.71   370.2  630.03
     380  631.39   389.7  636.14   399.5  642.43   409.2  647.79     419  651.82
#Mann= 3 , 0 , 0
       0     .06       0   231.3    .045       0   253.3     .06       0
Bank Sta=231.3,253.3
XS Rating Curve= 0 ,0
Exp/Cntr=0.3,0.1

Type RM Length L Ch R = 1 ,2862.9  ,84,77.1,70.4
XS GIS Cut Line= 3
      1773998.46       514790.63     1774109.137      514664.328
     1774281.012      514467.714
#Sta/Elev= 30
       0  627.01    18.7  625.01    37.3  622.77      56  621.33      84  619.65
   102.6  618.96   130.6  618.42   167.9  616.92   187.3  616.35   206.6  615.57
     226  615.33   235.6  614.98   245.3  614.36     255  612.53   263.8  610.08
   274.3     608     284  607.62   293.7  607.98     313  610.43   322.7  610.94
   332.4  612.28   351.7  618.47   361.4  619.23     371  622.22   380.7  628.49
   390.4  635.33   400.1   641.8   409.7  646.47   419.4  650.26   429.1  654.24
#Mann= 3 , 0 , 0
       0     .06       0   263.8    .045       0   293.7     .06       0
Bank Sta=263.8,293.7
XS Rating Curve= 0 ,0
Exp/Cntr=0.3,0.1

Type RM Length L Ch R = 1 ,2785.7  ,77.4,55.5,43.2
XS GIS Cut Line= 4
     1774218.512      514881.776     1774197.679       514728.13
     1774266.689      514575.787     1774305.752      514511.985
#Sta/Elev= 30
       0  624.74    19.4     623    48.4  621.19    67.8  620.28    77.5  620.06
    87.2  620.06    96.9   619.8   116.3  617.99   135.7  616.51   145.4  616.13
   184.6  615.71   204.2  615.07   214.1  614.89   243.6  614.73   253.4  613.16
   263.3  611.17   268.6  610.32     283  608.13   292.8  607.23   302.6  607.82
   312.5  610.46   322.3  614.77   331.6  617.04     341  617.15   350.4  619.06
   359.7  625.27     369  633.22   378.4  640.03   387.8  644.86   397.1  648.25
#Mann= 3 , 0 , 0
       0     .06       0   268.6    .045       0   292.8      .1       0
Bank Sta=268.6,292.8
XS Rating Curve= 0 ,0
Exp/Cntr=0.3,0.1

Type RM Length L Ch R = 1 ,2730.2  ,60.4,60.2,50.3
XS GIS Cut Line= 3
     1774383.877      514867.453     1774291.429       514621.36
     1774339.606      514556.255
#Sta/Elev= 28
       0  619.49    19.5  617.47    29.2  616.77      39  616.32    48.7  616.03
    87.6  615.24   107.1  614.69   116.8  614.49   126.6  614.53   155.8  615.41
     185  615.14   194.7   615.3   204.5  614.56   214.2  612.24   223.9  609.58
   233.7   607.5   235.3  607.38   243.4  606.76   253.2  606.82   262.9   607.3
   271.9  610.75   280.9   616.2   289.9  617.02   298.9  616.66   307.9  617.14
   316.9  621.96   334.9  636.55   343.9  642.64
#Mann= 3 , 0 , 0
       0     .06       0   235.3    .045       0   262.9      .1       0
#XS Ineff= 2 , 0
          194.58  619.87
Permanent Ineff=
       F       F
Bank Sta=235.3,262.9
XS Rating Curve= 0 ,0
Exp/Cntr=0.3,0.1

Type RM Length L Ch R = 1 ,2670    ,212,224.3,236.1
XS GIS Cut Line= 3
     1774434.658      514879.172     1774331.793      514605.735
      1774379.97       514540.63
#Sta/Elev= 30
       0  618.01     9.7  616.88    19.5  616.09    77.9  613.73    97.4  613.16
   126.6  612.47   136.3  612.48   155.8   613.1   175.3  613.42     185  613.36
   194.8  612.02   204.5  610.25   214.2  608.07     224  606.97   233.7  607.02
   237.3  607.58   243.4  608.54   253.2  611.33   262.9  614.56   272.7  616.57
   282.4  616.73   292.2  616.51   301.1  618.06   310.1   623.3   328.1  637.78
   337.1  643.06   346.1   646.4   355.1  649.28   364.1  653.19   373.1  659.81
#Mann= 3 , 0 , 0
       0     .06       0   214.2    .045       0   237.3      .1       0
#XS Ineff= 2 , 0
          166.29   621.5
Permanent Ineff=
       F       F
Bank Sta=214.2,237.3
XS Rating Curve= 0 ,0
Exp/Cntr=0.3,0.1

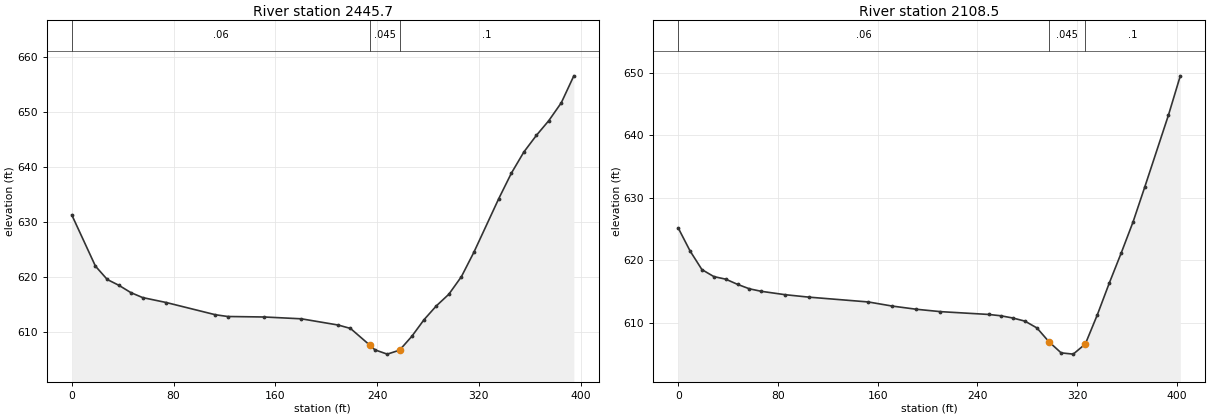
Type RM Length L Ch R = 1 ,2445.7  ,341.3,337.2,332.8
XS GIS Cut Line= 4
     1774570.075      514954.693     1774573.981      514880.474
     1774568.772      514668.235     1774545.335      514562.766
#Sta/Elev= 30
       0  631.31    18.6     622    27.9  619.57    37.2  618.49    46.4  617.19
    55.7  616.28    74.3  615.38   112.9  613.16   122.6  612.84   151.5  612.75
   180.5  612.42   209.4  611.29   219.1  610.67   234.4  607.61   238.4  606.77
     248     606   257.7  606.72   267.3  609.23     277  612.28   286.6  614.77
   296.4  616.88   306.3  620.08   316.1  624.51   335.7  634.28   345.6   638.9
   355.4  642.74   365.2  645.75     375  648.44   384.8  651.68   394.7  656.59
#Mann= 3 , 0 , 0
       0     .06       0   234.4    .045       0   257.7      .1       0
Bank Sta=234.4,257.7
XS Rating Curve= 0 ,0
Exp/Cntr=0.3,0.1

Type RM Length L Ch R = 1 ,2108.5  ,177.1,180,182.5
XS GIS Cut Line= 4
     1774926.845       514946.88     1774928.147      514794.537
     1774889.085      514614.849     1774883.877      514548.443
#Sta/Elev= 30
       0  625.15     9.5  621.48      19   618.5    28.6  617.38    38.1  616.97
    47.6  616.14    57.1  615.43    66.6  615.03    85.7  614.49   104.7   614.1
   152.4  613.33   171.7  612.67   191.1  612.16   210.4  611.78   249.1  611.33
   258.8  611.12   268.5  610.76   278.2  610.26   287.8  609.17   297.5  606.95
   307.2  605.19   316.9  604.99   326.6  606.61   336.2  611.26   345.8  616.34
   355.3  621.11   364.8  626.07   374.3  631.71   393.3   643.2   402.8  649.47
#Mann= 3 , 0 , 0
       0     .06       0   297.5    .045       0   326.6      .1       0
Bank Sta=297.5,326.6
XS Rating Curve= 0 ,0
Exp/Cntr=0.3,0.1