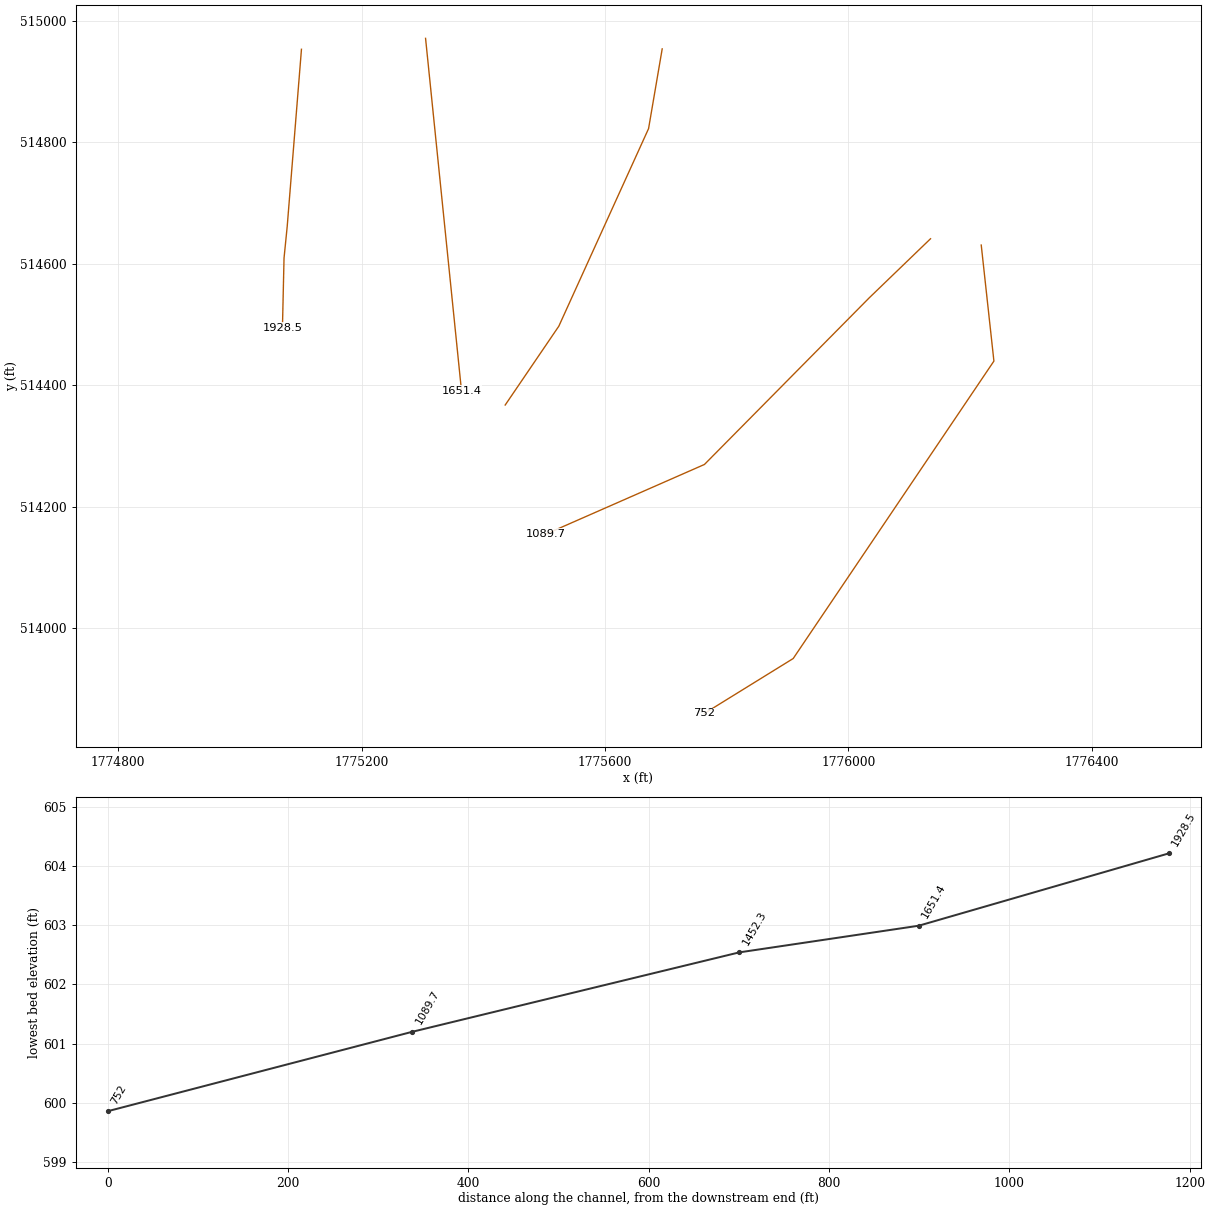
HEC-RAS study TWOMILECK.prj: TWOMILECK

--- TWOMILECK.g01 (geometry) --- (continued)

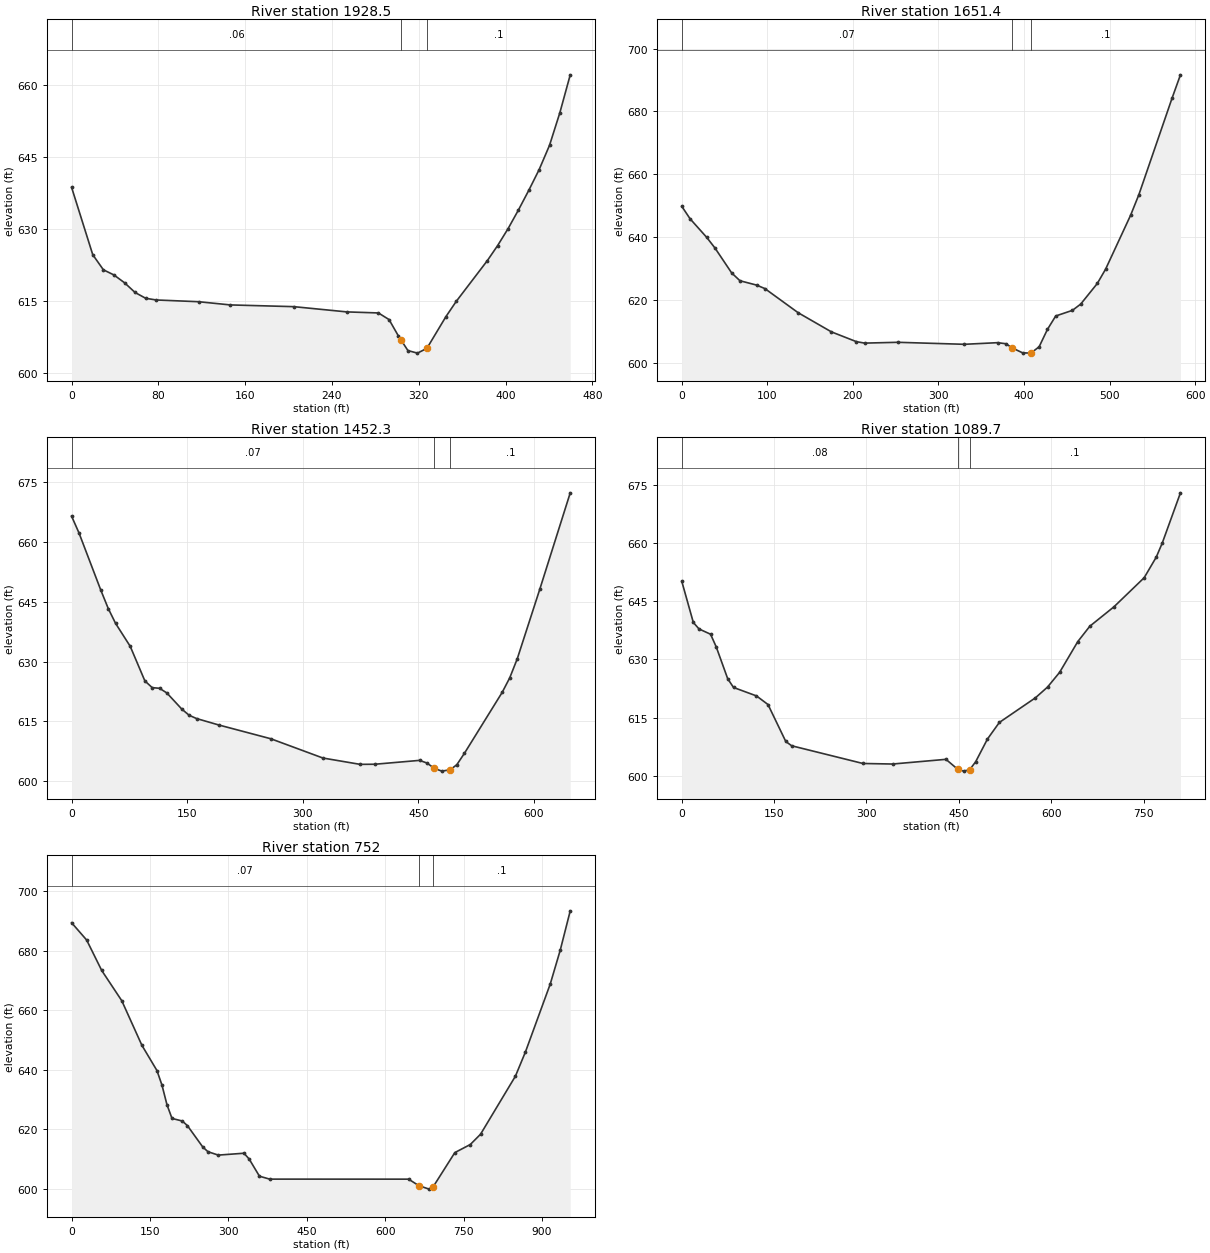
Type RM Length L Ch R = 1 ,1928.5  ,272.6,277.2,281.7
XS GIS Cut Line= 4
     1775101.325      514953.391     1775077.887      514661.724
     1775072.679      514609.641     1775070.075      514495.058
#Sta/Elev= 30
       0   638.7    19.5  624.69    29.3  621.55      39  620.48    48.8  618.85
    58.5  616.83    68.3  615.62      78  615.27     117  614.91   146.3  614.24
   204.8  613.88   253.6  612.79   282.8  612.57   292.6  611.19   301.3  607.75
   303.9  606.85     310  604.74   318.8  604.21   327.5  605.21     345   611.8
   354.5  614.97   383.2  623.46   392.7   626.6   402.3  630.11   411.8  633.97
   421.4  638.09   430.9  642.38   440.5  647.45     450  654.21   459.6  662.12
#Mann= 3 , 0 , 0
       0     .06       0   303.9    .045       0   327.5      .1       0
Bank Sta=303.9,327.5
XS Rating Curve= 0 ,0
Exp/Cntr=0.3,0.1

Type RM Length L Ch R = 1 ,1651.4  ,211,199.1,184.2
XS GIS Cut Line= 2
     1775305.273      514971.399     1775364.301      514391.538
#Sta/Elev= 30
       0  649.73     9.7  645.77    29.1  639.86    38.9  636.42    58.3  628.53
      68  626.04    87.4  624.66    97.1  623.55     136  615.86   174.9  609.76
     204  606.65   213.7  606.18   252.6  606.44   330.3   605.8   369.1  606.32
   378.9  605.98   386.3  604.64   398.3  603.09     408  602.99   417.7  605.01
   427.4  610.54   437.1  614.82   456.6  616.61   466.3  618.61   485.7  625.17
   495.4  629.73   524.6  646.88   534.3  653.46   573.1   684.2   582.9  691.63
#Mann= 3 , 0 , 0
       0     .07       0   386.3    .045       0     408      .1       0
Bank Sta=386.3,408
XS Rating Curve= 0 ,0
Exp/Cntr=0.3,0.1

Type RM Length L Ch R = 1 ,1452.3  ,370.8,362.6,357.2
XS GIS Cut Line= 4
     1775694.162      514954.038     1775671.762      514822.804
     1775524.294      514497.624      1775436.16      514367.856
#Sta/Elev= 30
       0  666.51     9.5  662.36      38  647.91    47.6  643.33    57.1  639.61
    76.1  633.85    95.1  625.18   104.6  623.49   114.1  623.33   123.6  622.16
   142.8  618.15   152.4  616.57   162.1  615.74     191  614.12   258.6  610.66
   326.1  605.83   374.4  604.24   393.7  604.27   451.6  605.24   461.2  604.57
   470.9  603.21   480.5  602.54   491.4  602.89     500  604.17   509.8  607.02
   558.8  622.31   568.6  625.96   578.4  630.76   607.8  648.32   647.1  672.38
#Mann= 3 , 0 , 0
       0     .07       0   470.9    .045       0   491.4      .1       0
Bank Sta=470.9,491.4
XS Rating Curve= 0 ,0
Exp/Cntr=0.3,0.1

Type RM Length L Ch R = 1 ,1089.7  ,333.3,337.7,341.8
XS GIS Cut Line= 4
     1776135.134      514641.538      1776034.44      514544.316
     1775763.606      514270.011      1775503.19      514155.427
#Sta/Elev= 30
       0  650.08    18.7  639.51      28  637.83    46.7  636.48      56  633.18
    74.6  624.99      84  622.76   121.3  620.58     140  618.36   168.9  608.84
   178.5  607.73   294.2  603.17   342.4  603.03   429.1  604.24   448.4  601.65
     458   601.2   467.6  601.58   477.3   603.6   496.5  609.47   515.8  613.74
   574.5   620.1   594.1  622.86   613.8  626.67   643.2  634.57   662.8  638.54
     702  643.54   751.1  651.04   770.7  656.34   780.5  659.99     810  672.91
#Mann= 3 , 0 , 0
       0     .08       0   448.4    .045       0   467.6      .1       0
Bank Sta=448.4,467.6
XS Rating Curve= 0 ,0
Exp/Cntr=0.3,0.1

Type RM Length L Ch R = 1 ,752     ,760,752,743.9
XS GIS Cut Line= 4
     1776218.468      514631.122     1776239.301      514440.149
      1775909.44      513950.566     1775763.606      513860.288
#Sta/Elev= 30
       0  689.35    28.8  683.54    57.6  673.32      96  663.15   134.5  648.17
   163.3  639.69   172.9   634.8   182.5  628.19   192.1  623.61   211.8  622.74
   221.6  621.18   251.1  613.98     261  612.42   280.7  611.29   329.8  611.92
   339.7  609.98   359.4   604.2     379  603.22   644.7  603.21   664.4  601.02
     684  599.86   691.8  600.66   733.2  612.13   762.8  614.85   782.4   618.3
   849.1   637.8   868.2   645.9   915.8  668.79   934.9  680.15     954  693.35
#Mann= 3 , 0 , 0
       0     .07       0   664.4    .045       0   691.8      .1       0
Bank Sta=664.4,691.8
XS Rating Curve= 0 ,0
Exp/Cntr=0.3,0.1

Chan Stop Cuts=-1
Use User Specified Reach Order=0
Composite Channel Slope=5